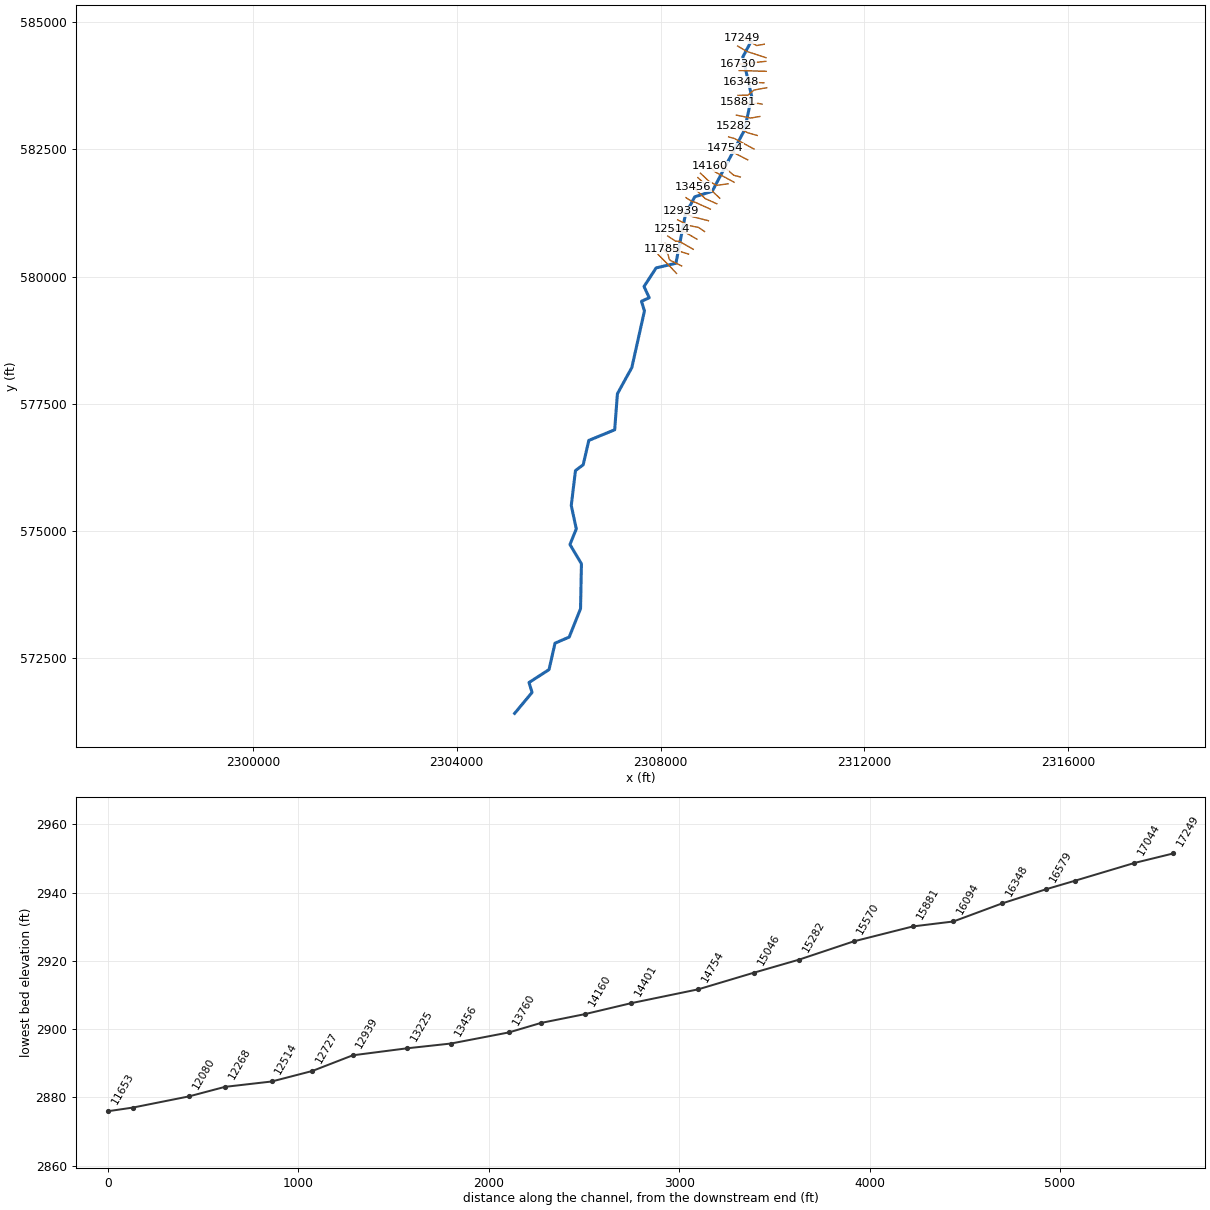
--- MNTNLCKCK.prj (project) ---

Proj Title=MNTNLCKCK
Current Plan=p01
Default Exp/Contr=0,0
English Units
Geom File=g01
Flow File=f01
Plan File=p01
Background Map Layer=Inundation Boundary (01pct Value_0)
Background Map Layer=Inundation Boundary (01pct Value_0)
BEGIN DESCRIPTION:
----------MODEL BY WOOD PLC 2021----------
Stream Name: Mountain Lick Creek
Flood Zone: Enhanced Approximate
Pocahontas County, WV
HEC-RAS Version: RAS 6.1
Vertical Datum: NAVD88
Projection: NAD 1983 StatePlane West Virginia S FIPS 4702 (US Feet)
Terrain: 1-meter LIDAR (FEMA Region III 3DEP collected 2016-2018)
Land Use: 2019 NLCD
Hydrologic Method:
WV SIR2010-5033 regression equations
Model Notes:
END DESCRIPTION:
DSS File=dss
DSS Export Rating Curves= 0
DSS Export Rating Curve Sorted= 0
DSS Export Volume Flow Curves= 0
DXF OffsetX= 0
DXF OffsetY= 0
DXF ScaleX= 0
DXF ScaleY= 0

--- MNTNLCKCK.p01 (plan) ---

Plan Title=Floodplain
Program Version=6.10
Short Identifier=Floodplain
Geom File=g01
Flow File=f01
Subcritical Flow
K Sum by GR= 0
Std Step Tol= 0.01
Critical Tol= 0.01
Num of Std Step Trials= 20
Max Error Tol= 0.3
Flow Tol Ratio= 0.001
Split Flow NTrial= 30
Split Flow Tol= 0.02
Split Flow Ratio= 0.02
Log Output Level= 0
Friction Slope Method= 1
Unsteady Friction Slope Method= 2
Unsteady Bridges Friction Slope Method= 1
Parabolic Critical Depth
Global Vel Dist= 0 , 0 , 0
Global Log Level= 0
CheckData=True
Encroach Param=-1 ,0,0, 0
Computation Interval=0.1SEC
Output Interval=1SEC
Instantaneous Interval=Max Profile
Mapping Interval=1HOUR
Computation Time Step Use Courant=        0
Computation Time Step Use Time Series=    0
Computation Time Step Count To Double=0
Computation Time Step Max Doubling=0
Computation Time Step Max Halving=0
Computation Time Step Residence Courant=0
Run HTab= 0
Run UNet= 0
Run Sediment= 0
Run PostProcess= 0
Run WQNet= 0
Run RASMapper=-1
UNET Theta= 0
UNET Theta Warmup= 0
UNET ZTol= 0
UNET ZSATol= 0
UNET MxIter= 0
UNET Max Iter WO Improvement= 0
UNET MaxInSteps= 0
UNET DtIC= 0
UNET DtMin= 0
UNET MaxCRTS= 0
UNET WFStab= 0
UNET SFStab= 0
UNET WFX= 1
UNET SFX= 1
UNET Gravity=32.174
UNET 1D Methodology=Finite Difference
UNET DSS MLevel= 1
UNET Pardiso=0
UNET DZMax Abort= 0
UNET Use Existing IB Tables= 0
UNET Froude Reduction=False
UNET Froude Limit= 0
UNET Froude Power= 0
UNET D1 Cores= 0
UNET WindReference=Eulerian
UNET WindDragFormulation=Hsu (1988)
UNET D2 Coriolis=0
UNET D2 Cores= 0
UNET D2 Theta= 1
UNET D2 Theta Warmup= 1
UNET D2 Z Tol= 0.01
UNET D2 Volume Tol= 0.01
UNET D2 Max Iterations= 20
UNET D2 Equation= 0
UNET D2 RampUpFraction=0.1
UNET D2 TimeSlices= 1
UNET D2 Turbulence Formulation=Non-Conservative (original)
UNET D2 Eddy Viscosity=0.3
UNET D2 Transverse Eddy Viscosity=0.1
UNET D2 Smagorinsky Mixing=0
UNET D2 BCVolumeCheck=0
UNET D2 Cores=0
UNET D2 SolverType=PARDISO (Direct)
UNET D2 Minimum Iterations= 2147483647
UNET D2 Maximum Iterations= 2147483647
UNET D2 Restart Number= 10
UNET D2 Relaxation Coeff=1.3
UNET D2 SOR Precondition Iterations= 10
UNET D2 ILUT Maximum Fill= 8
UNET D2 ILUT Tolerance=1E-08
UNET D1D2 MaxIter= 0
UNET D1D2 ZTol=0.01
UNET D1D2 QTol=0.1
UNET D1D2 MinQTol=1
DSS File=dss
Write IC File= 0
Write IC File at Fixed DateTime=0
Write IC File at Sim End=0
Echo Input=False
Echo Parameters=False
Echo Output=False
Write Detailed= 0
HDF Write Warmup=0
HDF Write Time Slices=0
HDF Flush=0
HDF Compression= 1
HDF Chunk Size= 1
HDF Spatial Parts= 1
HDF Use Max Rows=0
HDF Fixed Rows= 1
Calibration Method= 0
Calibration Iterations= 20
Calibration Max Change=0.05
Calibration Tolerance=0.2
Calibration Maximum=1.5
Calibration Minimum=0.5
Calibration Optimization Method= 1
WQ AD Non Conservative
WQ ULTIMATE=-1
WQ Max Comp Step=1HOUR
WQ Output Interval=15MIN
WQ Output Selected Increments= 0
WQ Output face flow=0
WQ Output face velocity=0
WQ Output face area=0
WQ Output face dispersion=0
WQ Output cell volume=0
WQ Output cell surface area=0
WQ Output cell continuity=0
WQ Output cumulative cell continuity=0
WQ Output face conc=0
WQ Output face dconc_dx=0
WQ Output face courant=0
WQ Output face peclet=0
WQ Output face adv mass=0
WQ Output face disp mass=0
WQ Output cell mass=0
WQ Output cell source sink temp=0
WQ Output nsm pathways=0
WQ Output nsm derived pathways=0
WQ Create Restart=0
WQ Fixed Restart=0
WQ System Summary=0
WQ Write To DSS=0
Sorting and Armoring Iterations= 10
XS Update Threshold= 0.02
Bed Roughness Predictor= 0
Hydraulics Update Threshold= 0.02
Energy Slope Method= 1
Volume Change Method= 1
Sediment Retention Method= 0
Sediment TS Multiplier= 1
Warm Up Method= 0
XS Weighting Method= 0
Number of US Weighted Cross Sections= 1
Number of DS Weighted Cross Sections= 1
Upstream XS Weight=0
Main XS Weight=1
Downstream XS Weight=0
Number of DS XS's Weighted with US Boundary= 1
Upstream Boundary Weight= 1
Weight of XSs Associated with US Boundary= 0
Number of US XS's Weighted with DS Boundary= 1
Downstream Boundary Weight= 0.5
Weight of XSs Associated with DS Boundary= 0.5
Percentile Method= 0
Sediment Output Level= 3
Mass or Volume Output= 0
Output Increment Type= 1
Profile and TS Output Increment= 1
Transport Output Increment 1
XS Output Flag= 0
XS Output Increment= 10
Read HDF5 Sediment Hotstart= 0
Sediment Hotstart Type= 0
Write Gradation File= 0
Read Gradation Hotstart= 0
Write HDF5 File= 1
Write Binary Output= 1
Write DSS Sediment File= 0
DSS Sediment Output Type= 1
SV Curve= 0
Specific Gage Flag= 0
Subcell Erosion Methods= 0
Subcell Deposition Methods= 0
Advection Scheme= 1
Matrix Solver= 0
Implicit Weighting Factor= 1
Maximum Outer Loop Convergence Iterations= 5
Convergence Maximum Absolute= 0.001
Convergence RMSE= 0.0001
Grain Fractions Max Abs Error= 0.001
Max Subgrid Regions= 1
Max Subgrid Length Scale= 3.402823E+38
Initial Layer Thickness= 3.402823E+38
Min Layer Thickness= 3.402823E+38
Max Layer Thickness= 3.402823E+38
Number of Layers= 5

--- MNTNLCKCK.f01 (steady flow) ---

Flow Title=Flow
Program Version=6.10
Number of Profiles= 6
Profile Names=01pct,10pct,04pct,02pct,0_2pct,01plus
River Rch & RM=MNTNLCKCK,Main,17249
     641     340     452     543     894     948
River Rch & RM=MNTNLCKCK,Main,13927
     801     429     567     681    1110    1190
River Rch & RM=MNTNLCKCK,Main,12080
     893     480     633     759    1240    1320
River Rch & RM=MNTNLCKCK,Main,5933
    1530     840    1100    1310    2100    2260
Boundary for River Rch & Prof#=MNTNLCKCK,Main            , 1
Up Type= 0
Dn Type= 3
Dn Slope=0.00773
Boundary for River Rch & Prof#=MNTNLCKCK,Main            , 2
Up Type= 0
Dn Type= 3
Dn Slope=0.00773
Boundary for River Rch & Prof#=MNTNLCKCK,Main            , 3
Up Type= 0
Dn Type= 3
Dn Slope=0.00773
Boundary for River Rch & Prof#=MNTNLCKCK,Main            , 4
Up Type= 0
Dn Type= 3
Dn Slope=0.00773
Boundary for River Rch & Prof#=MNTNLCKCK,Main            , 5
Up Type= 0
Dn Type= 3
Dn Slope=0.00773
Boundary for River Rch & Prof#=MNTNLCKCK,Main            , 6
Up Type= 0
Dn Type= 3
Dn Slope=0.00773
DSS Import GetInterval= 0
DSS Import GetPeak= 0
DSS Import FillOption= 0

--- MNTNLCKCK.g01 (geometry) ---

Geom Title=Geometry
Program Version=6.10

River Reach=MNTNLCKCK       ,Main
Reach XY= 30
     2309776.695      584617.792     2309613.118      584310.134
     2309788.995      583531.6692309644.72755676582872.408525018
     2309013.185      581673.692     2308670.393      581565.127
     2308488.231      581221.888     2308300.245      580259.675
     2307912.554      580168.968     2307674.942      579803.722
     2307776.682      579583.1522307624.75327152579513.633271516
     2307683.242      579324.1272307435.65687785578212.777909495
     2307152.718      577697.258     2307099.154      576990.479
      2306591.42      576781.4832306481.15315757576303.137475102
     2306329.602       576189.32     2306247.254      575503.271
     2306345.828      575044.734     2306221.529      574737.716
     2306446.658      574359.339     2306429.275      573477.803
      2306207.15      572920.557     2305928.374      572800.134
     2305810.847      572281.1522305418.20885451572027.911166273
2305477.86972897571833.330586932      2305136.08      571421.987

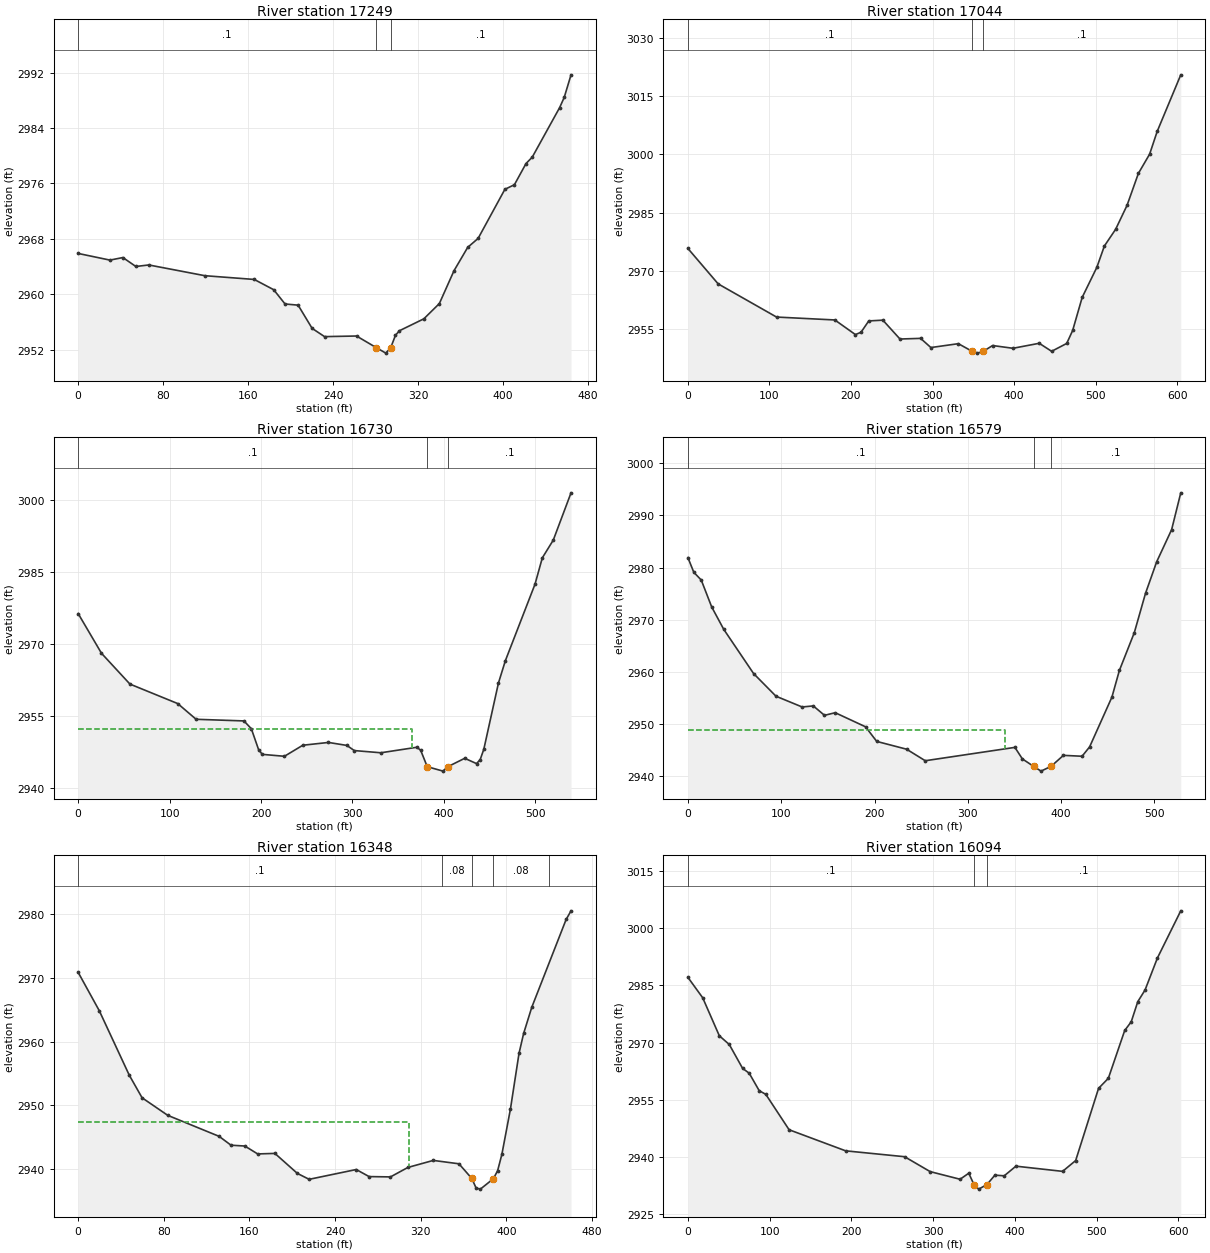
Type RM Length L Ch R = 1 ,17249   ,204.9,204.9,204.9
XS GIS Cut Line= 4
2310033.66659538584561.0537729892309886.11966218584535.146925126
2309698.65019588584640.450844967 2309606.2053576584676.601761602
#Sta/Elev= 30
       0  2965.9    29.9 2964.94    42.1 2965.31    54.3 2964.02    66.5 2964.24
   119.3 2962.69   165.8 2962.15   184.1 2960.67   194.8 2958.61   207.1 2958.44
   220.3 2955.09     232  2953.9   262.1 2953.99   280.5 2952.33   289.7 2951.52
   294.3 2952.31   298.8  2954.1   302.5 2954.75   325.5 2956.47   340.1 2958.67
   353.9 2963.41   366.8 2966.78   376.6 2968.07   401.8 2975.15   410.8 2975.82
   421.7 2978.87   427.6  2979.8   453.4 2986.95   457.7 2988.42   464.1 2991.67
#Mann= 3 ,-1,0
       0      .1       0   280.5    .045       0   294.3      .1       0
Bank Sta=280.5,294.3
XS Rating Curve= 0 ,0
Exp/Cntr=0.3,0.1

Type RM Length L Ch R = 1 ,17044   ,301.1,314.7,323.5
XS GIS Cut Line= 3
2310067.46355917584296.7838473552309696.36416264584417.943609263
2309511.19546991584525.387171709
#Sta/Elev= 30
       0 2975.73    37.1 2966.59   108.7 2958.03   180.2 2957.28   205.4 2953.51
   212.3  2954.1   221.8 2957.03   239.1 2957.23   260.1 2952.36   285.4 2952.53
     298 2950.16   331.7 2951.16   348.5  2949.2     355 2948.72   362.1 2949.17
   373.7 2950.68   398.7 2949.97   430.9 2951.26   446.1 2949.19   464.6 2951.22
   471.9 2954.57   483.6 2963.12   501.6 2970.88   510.8 2976.37   524.6 2980.68
   538.6 2986.86   552.5  2995.1   566.3 3000.08   575.6 3005.96   604.5 3020.55
#Mann= 3 ,-1,0
       0      .1       0   348.5    .045       0   362.1      .1       0
Bank Sta=348.5,362.1
XS Rating Curve= 0 ,0
Exp/Cntr(USF)=0,0
Exp/Cntr=0.3,0.1

Type RM Length L Ch R = 1 ,16730   ,153.6,150.3,143.9
XS GIS Cut Line= 4
2310064.47406918584224.9797424392309702.23848757584186.586955675
 2309645.3094202584174.1000632852309528.72172478584172.576041123
#Sta/Elev= 30
       0 2976.26    25.5    2968    56.6 2961.59   108.9 2957.53     129 2954.26
   181.3 2953.92   189.4  2952.3   197.4 2947.91   201.4 2946.96   225.6 2946.56
   245.7 2948.86   273.8 2949.44   293.9 2948.82     302 2947.75   331.1 2947.29
   370.5 2948.44   374.6 2947.82   381.82944.397   399.1 2943.47   404.1 2944.37
   422.8 2946.14   435.7 2945.04   439.7 2945.85   443.7 2948.03   459.7 2961.81
   467.3 2966.47   499.7 2982.39   507.7 2987.87   519.7 2991.57   539.1  3001.4
#Mann= 3 ,-1,0
       0      .1       0   381.8    .045       0   404.1      .1       0
#XS Ineff= 2 , 0
          365.41 2952.14
Permanent Ineff=
       F       F
Bank Sta=381.8,404.1
XS Rating Curve= 0 ,0
Exp/Cntr=0.3,0.1

Type RM Length L Ch R = 1 ,16579   ,231.4,231.3,231.5
XS GIS Cut Line= 2
 2310070.5116035584029.3179578612309542.43792424584043.796168403
#Sta/Elev= 30
       0  2981.9     6.3 2979.09    14.3  2977.6    25.5 2972.44    38.4 2968.16
    70.4 2959.69    94.4 2955.35   122.4 2953.29   134.4 2953.49   146.4 2951.69
   157.9 2952.19   190.4 2949.49   202.4 2946.69   234.4  2945.2   254.4 2942.99
   350.5 2945.55   358.5 2943.34   370.5 2941.92   378.5    2941   389.3 2941.92
   402.5 2944.02   422.5 2943.85   430.6 2945.65   454.5 2955.18   462.5 2960.29
   478.5 2967.53   490.5 2975.06   502.5 2981.11   518.5 2987.26   528.3 2994.31
#Mann= 3 ,-1,0
       0      .1       0   370.5    .045       0   389.3      .1       0
#XS Ineff= 2 , 0
          339.72 2948.97
Permanent Ineff=
       F       F
Bank Sta=370.5,389.3
XS Rating Curve= 0 ,0
Exp/Cntr(USF)=0,0
Exp/Cntr=0.3,0.1

Type RM Length L Ch R = 1 ,16348   ,240.3,254.4,268.7
XS GIS Cut Line= 2
2310027.83898295583803.7626778322309567.58428992583818.240888374
#Sta/Elev= 30
       0 2970.89    19.7 2964.87    47.7 2954.75    59.7 2951.19    83.7 2948.43
   131.7 2945.13   142.8 2943.74   155.7 2943.61   167.7 2942.37   183.8 2942.45
   204.8 2939.31   215.8 2938.38   259.8 2939.92   271.8 2938.81   291.8 2938.76
   308.1 2940.25   331.8 2941.35   355.8 2940.82   367.8 2938.51   371.8 2937.01
   375.8 2936.84   387.9 2938.47   391.9 2939.73   395.9 2942.32   403.9 2949.44
   411.9 2958.17   416.2 2961.29   423.8  2965.4   455.9  2979.2   460.5 2980.56
#Mann= 5 ,-1,0
       0      .1       0     340     .08       0   367.8    .045       0
   387.9     .08       0     440      .1       0
#XS Ineff= 2 , 0
          308.97 2947.44
Permanent Ineff=
       F       F
Bank Sta=367.8,387.9
XS Rating Curve= 0 ,0
Exp/Cntr(USF)=0,0
Exp/Cntr=0.3,0.1

Type RM Length L Ch R = 1 ,16094   ,224,212.5,199
XS GIS Cut Line= 4
2310081.94176972583706.9872705222309833.52615725583661.266605651
2309716.93846183583562.2051650972309519.57759181583556.871087529
#Sta/Elev= 30
       0  2987.1    18.1 2981.74    38.4 2971.79    50.6  2969.5    66.9 2963.24
      75 2961.96    87.2 2957.39    95.3 2956.42   123.8 2947.14     193 2941.61
   265.1 2940.07   296.4 2936.16     333 2934.16   343.6 2935.74   350.1 2932.71
   355.8 2931.57   365.92932.777   375.6 2935.24     387 2935.06   401.3 2937.59
   458.4 2936.23   474.4 2939.06   502.4 2957.99   514.4 2960.64   534.4 2973.17
   542.4 2975.46   550.4 2980.73   559.3 2983.79   574.4 2992.17     603 3004.55
#Mann= 3 ,-1,0
       0      .1       0   350.1    .045       0   365.9      .1       0
Bank Sta=350.1,365.9
XS Rating Curve= 0 ,0
Exp/Cntr(USF)=0,0
Exp/Cntr=0.3,0.1

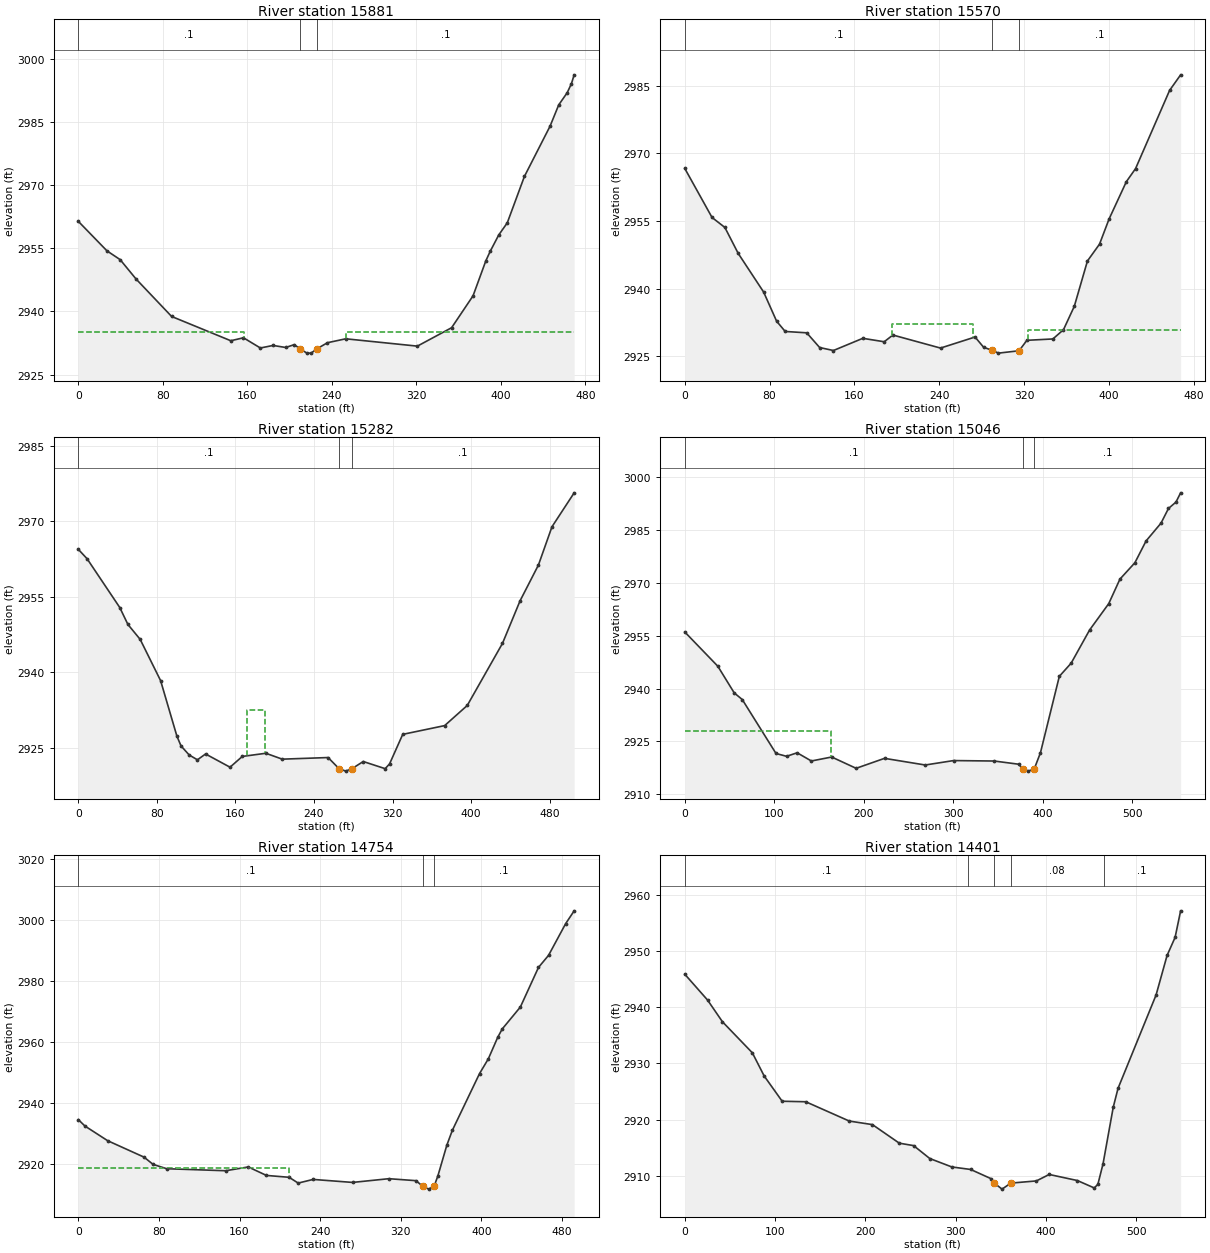
Type RM Length L Ch R = 1 ,15881   ,309.1,311.6,304.5
XS GIS Cut Line= 4
2309991.06802377583384.4307597912309910.76842856 583399.31075481
 2309722.2725394  583396.08674942309525.67368046583427.329203729
#Sta/Elev= 30
       0 2961.39    27.1 2954.39    39.6  2952.3    54.6 2947.72    88.3 2938.82
   144.3 2933.06   156.3 2933.76   172.3 2931.34   184.3 2931.94   196.3 2931.46
   204.3 2932.13  209.96 2931.15   216.3 2930.12   220.3 2930.12  226.02 2931.17
   235.8 2932.59   253.1 2933.52   320.9 2931.78   353.3 2936.15   373.6 2943.72
   385.7 2952.02   389.8 2954.26   397.9 2958.15     406 2961.04   422.2 2972.04
   446.5 2983.98   454.7 2989.03   462.7 2991.91   466.7 2994.05   469.3 2996.16
#Mann= 3 ,-1,0
       0      .1       0  209.96    .045       0  226.02      .1       0
#XS Ineff= 2 , 0
          157.09  2935.2  253.19         2935.07
Permanent Ineff=
       F       F
Bank Sta=209.96,226.02
XS Rating Curve= 0 ,0
Exp/Cntr(USF)=0,0
Exp/Cntr=0.3,0.1

Type RM Length L Ch R = 1 ,15570   ,289.9,287.3,283.9
XS GIS Cut Line= 3
2309945.45711829583142.1677235722309772.37447578583111.957274292
2309486.04910423583169.007447209
#Sta/Elev= 30
       0 2966.65    25.7 2955.79    37.8 2953.58    50.4 2947.82    74.4 2939.25
    86.6 2932.81    94.7 2930.53     115 2930.23   127.2 2926.97   140.2 2926.31
   167.9 2929.01   188.1 2928.25   196.3 2929.74   241.2 2926.85   273.8  2929.3
   281.9 2927.02   290.1 2926.34   295.9 2925.73   315.32926.255   322.7 2928.57
   347.2 2928.87   357.2 2930.92   367.4  2936.1   379.8 2946.15   391.2 2949.88
   400.2 2955.45   416.5 2963.72   425.2 2966.62   457.3 2983.95   467.7  2987.4
#Mann= 3 ,-1,0
       0      .1       0   290.1    .045       0   315.3      .1       0
#XS Ineff= 2 ,-1
  195.18  271.59 2932.12  323.61   467.7 2930.95
Permanent Ineff=
       F       F
Bank Sta=290.1,315.3
XS Rating Curve= 0 ,0
Exp/Cntr(USF)=0,0
Exp/Cntr=0.3,0.1

Type RM Length L Ch R = 1 ,15282   ,236.9,236.8,235.8
XS GIS Cut Line= 3
2309896.77307699 582769.713640672309710.75770529 582822.80041266
2309431.94631747582961.740433128
#Sta/Elev= 30
       0 2964.46     8.9  2962.6    42.2  2952.9    50.5 2949.53      63 2946.56
    83.8 2938.36   100.4 2927.32   104.6 2925.38   112.9 2923.58   121.3 2922.62
   129.6 2923.78   154.5 2921.15     167 2923.29     191 2923.92   207.7 2922.75
   254.4 2923.07   265.42920.888   272.3 2920.37   278.72920.858   290.2 2922.28
   312.5 2920.86     317 2921.81   330.4 2927.68   373.1 2929.42   396.1 2933.42
     432 2945.77   449.9 2954.23   468.6 2961.34   482.4 2968.95     505  2975.7
#Mann= 3 ,-1,0
       0      .1       0   265.4    .045       0   278.7      .1       0
#XS Ineff= 1 ,-1
     172     190 2932.62
Permanent Ineff=
       F
Bank Sta=265.4,278.7
XS Rating Curve= 0 ,0
Exp/Cntr(USF)=0,0
Exp/Cntr=0.3,0.1

Type RM Length L Ch R = 1 ,15046   ,290,291.5,287.4
XS GIS Cut Line= 3
2309832.76414617582503.7717733392309452.52061666582707.990743095
2309335.17091016582742.281241748
#Sta/Elev= 30
       0 2956.08    36.9 2946.35    55.2 2938.78    64.2 2936.89   101.9 2921.56
   113.7 2920.76   125.5 2921.76   141.4 2919.43   164.1 2920.56   191.4 2917.35
   223.1 2920.18   268.6 2918.29   300.3 2919.55   345.7 2919.42     373 2918.51
   377.5 2917.19   383.4 2916.55   390.3 2917.12   397.3 2921.76   418.4 2943.48
   431.6 2947.22   452.2 2956.64   473.6 2964.14   486.1  2971.1   502.8 2975.75
   515.3 2981.95     532 2987.01   540.3 2991.17   548.7 2992.99   553.9 2995.62
#Mann= 3 ,-1,0
       0      .1       0   377.5    .045       0   390.3      .1       0
#XS Ineff= 2 , 0
          163.46 2927.83
Permanent Ineff=
       F       F
Bank Sta=377.5,390.3
XS Rating Curve= 0 ,0
Exp/Cntr(USF)=0,0
Exp/Cntr=0.3,0.1

Type RM Length L Ch R = 1 ,14754   ,357.2,353.1,375.5
XS GIS Cut Line= 2
 2309710.0803621582290.408670608 2309272.6860015582515.963950637
#Sta/Elev= 30
       0 2934.48     6.6 2932.37    29.1 2927.57    65.2 2922.18    74.2  2919.8
    87.7 2918.38   146.2 2917.72   168.7 2918.96   186.7 2916.18   209.2 2915.57
   218.2 2913.67     233 2914.87   272.2 2913.89   308.2 2915.11   335.2 2914.46
   341.8 2912.61   347.9 2911.69   353.2 2912.74   356.8 2915.97   365.7 2926.06
   371.2 2930.97   398.2 2949.58   406.9  2954.4   416.2 2961.44   420.7  2964.2
   438.7 2971.39   456.7 2984.39   466.7 2988.35   483.7 2998.76   492.1 3002.94
#Mann= 3 ,-1,0
       0      .1       0   341.8    .045       0   353.2      .1       0
#XS Ineff= 2 , 0
          209.14 2918.56
Permanent Ineff=
       F       F
Bank Sta=341.8,353.2
XS Rating Curve= 0 ,0
Exp/Cntr(USF)=0,0
Exp/Cntr=0.3,0.1

Type RM Length L Ch R = 1 ,14401   ,235.6,241,214
XS GIS Cut Line= 3
 2309564.5362456581954.361783808 2309434.9943618 581987.89027138
2309119.52177419582257.642194117
#Sta/Elev= 30
       0 2945.89    25.2 2941.29    41.7 2937.42    74.8 2931.89    87.9 2927.76
   107.8 2923.27   133.9 2923.18   182.1 2919.74   207.7 2919.11   237.5  2915.8
   253.3 2915.37   271.2 2913.07   295.6 2911.57   316.5 2911.12   338.9 2909.49
   342.8 2908.67   351.2 2907.62   360.9 2908.69   389.2 2909.08   403.4 2910.23
   434.6 2909.15   453.3 2907.83   457.3 2908.48     463 2912.12   474.3  2922.2
   479.6 2925.56   521.7 2942.18   533.9 2949.23   542.8 2952.46   548.9 2957.18
#Mann= 5 ,-1,0
       0      .1       0  313.81     .08       0   342.8    .045       0
   360.9     .08       0  463.81      .1       0
Bank Sta=342.8,360.9
XS Rating Curve= 0 ,0
Exp/Cntr(USF)=0,0
Exp/Cntr=0.3,0.1

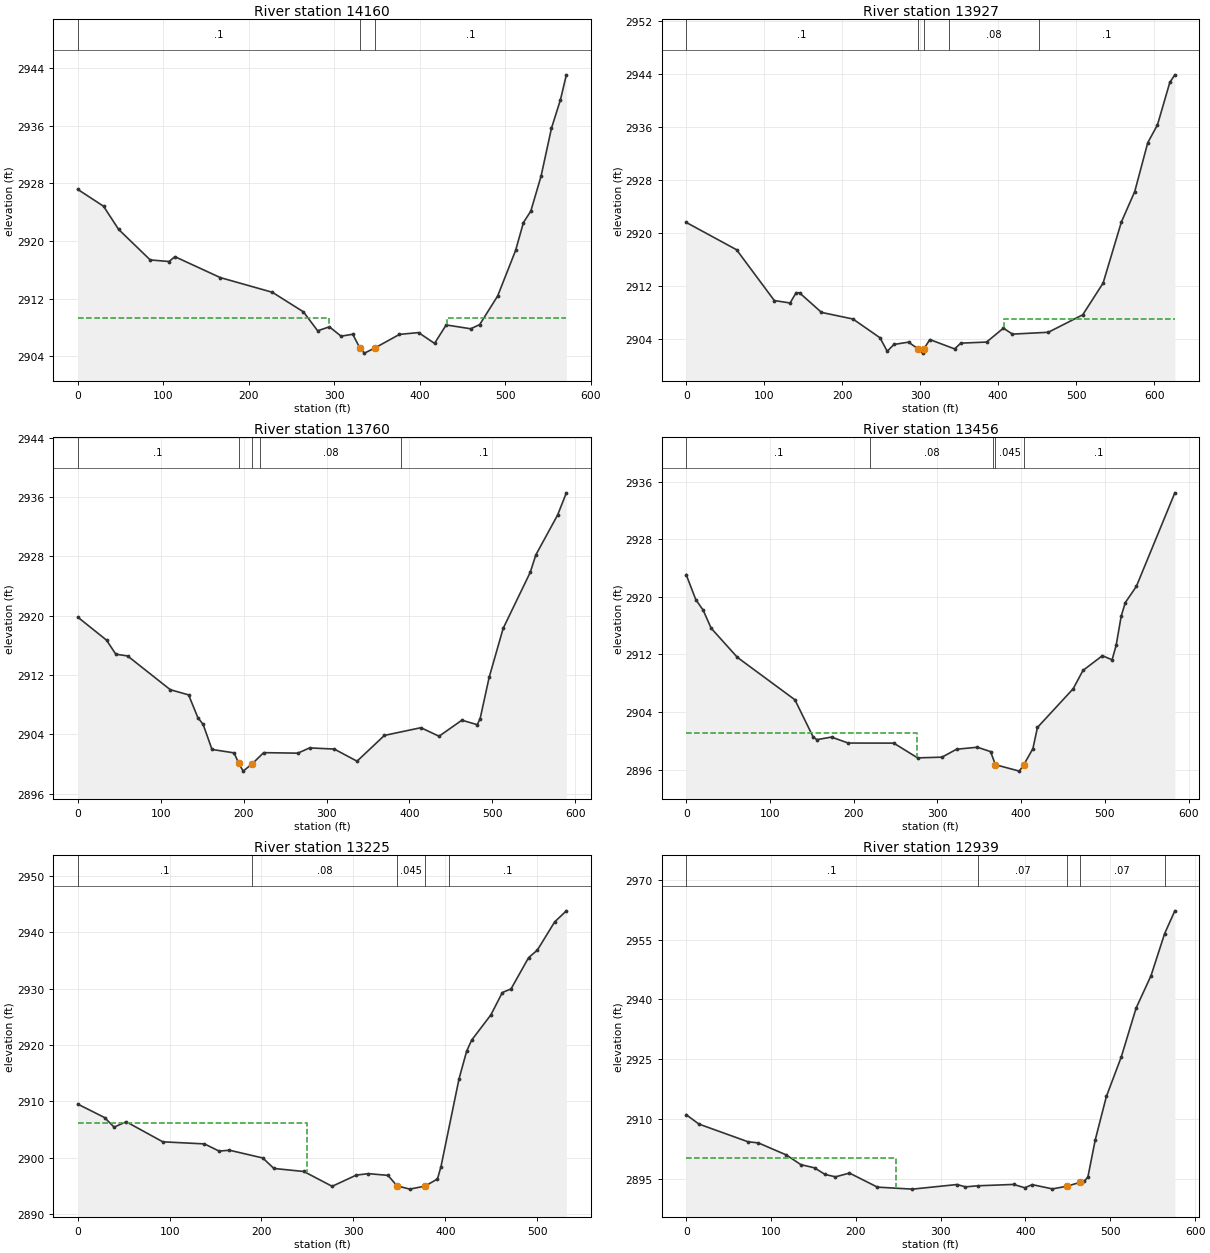
Type RM Length L Ch R = 1 ,14160   ,232.3,233.1,231.1
XS GIS Cut Line= 3
2309442.61447261581850.7282767672309058.56088769582060.281324092
2308971.69162444 582162.39080897
#Sta/Elev= 30
       0 2927.15    30.2 2924.81    47.8  2921.6    84.8 2917.36   106.8 2917.14
   113.7 2917.81   166.8 2914.91   227.7 2912.87     264 2910.16   280.7 2907.53
   294.4 2908.08   308.1 2906.78   321.7 2907.05     3302905.161   335.4 2904.43
   347.5 2905.14   376.4 2907.03   398.7 2907.28   417.4 2905.78     431 2908.34
   459.7 2907.81   470.2 2908.39   491.2 2912.35   512.2 2918.67   521.4 2922.55
     530 2924.13     542 2928.98   554.2 2935.64   564.7 2939.59   571.6 2943.04
#Mann= 3 ,-1,0
       0      .1       0     330    .045       0   347.5      .1       0
#XS Ineff= 2 , 0
          294.34  2909.3  432.12         2909.29
Permanent Ineff=
       F       F
Bank Sta=330,347.5
XS Rating Curve= 0 ,0
Exp/Cntr(USF)=0,0
Exp/Cntr=0.3,0.1

Type RM Length L Ch R = 1 ,13927   ,170.7,166.9,159.2
XS GIS Cut Line= 4
2309324.24875133581819.6551582372309099.26468739581790.291387918
 2308945.1691132581874.1126068492308782.54354051582028.530862376
#Sta/Elev= 30
       0 2921.56    64.6 2917.43     113 2909.76   133.2 2909.39     141 2910.94
   145.3 2910.93   173.5 2907.97   213.9 2906.97   248.6 2904.13   257.8  2902.1
   266.4 2903.13   285.1 2903.48   296.92902.499   303.3 2901.82     305 2902.48
   312.4 2903.87   344.2 2902.46   352.2 2903.33   385.2 2903.49   406.8 2905.59
   418.4 2904.69   464.4 2904.97   508.5 2907.61   534.6 2912.39   558.1 2921.63
   575.2 2926.22   591.9  2933.6   604.3 2936.27   620.2 2942.71   626.6 2943.84
#Mann= 5 ,-1,0
       0      .1       0   296.9    .045       0     305      .1       0
  336.89     .08       0  452.31      .1       0
#XS Ineff= 2 , 0
                           407.4         2906.93
Permanent Ineff=
       F       F
Bank Sta=296.9,305
XS Rating Curve= 0 ,0
Exp/Cntr(USF)=0,0
Exp/Cntr=0.3,0.1

Type RM Length L Ch R = 1 ,13760   ,294.4,304.3,307
XS GIS Cut Line= 2
2309161.43238365581537.5417224022308732.42014495581941.407595428
#Sta/Elev= 30
       0 2919.81    34.7 2916.71    45.9 2914.81    60.1 2914.58   111.6 2910.03
   133.7 2909.33   144.9 2906.26   151.2 2905.36   161.9 2901.98   188.5 2901.52
     194 2900.15   199.5 2899.06   210.5 2900.06   224.2 2901.55   265.4 2901.48
   279.6 2902.19   309.4 2902.03   336.8  2900.4   369.8 2903.87   413.8 2904.91
   435.7 2903.76   463.2 2905.92   481.7 2905.32   485.2 2906.12   496.1 2911.69
     513 2918.29   545.6 2925.83   552.4 2928.19   578.6 2933.55   589.2 2936.55
#Mann= 5 ,-1,0
       0      .1       0     194    .045       0   210.5      .1       0
     220     .08       0     390      .1       0
Bank Sta=194,210.5
XS Rating Curve= 0 ,0
Exp/Cntr(USF)=0,0
Exp/Cntr=0.3,0.1

Type RM Length L Ch R = 1 ,13456   ,210.7,230.6,238.6
XS GIS Cut Line= 3
 2309102.6728625  581428.32013412308877.43479487581528.667583377
2308633.35870439581760.810969188
#Sta/Elev= 30
       0 2923.09    11.5 2919.61    20.3 2918.15    29.8 2915.65    61.1  2911.6
   129.8 2905.71   151.6 2900.54     156 2900.17   173.5 2900.53   193.4  2899.7
   247.8 2899.69   276.3 2897.64   305.4 2897.74   322.8 2898.84   347.7 2899.12
   363.4 2898.51   369.2 2896.69   397.8  2895.8   402.9 2896.66   413.9 2898.91
   419.4 2901.87   462.1 2907.25   473.7 2909.78   496.9 2911.83   508.5 2911.26
   513.3 2913.25   519.4 2917.34   524.3 2919.21   537.5 2921.46   583.4 2934.45
#Mann= 5 ,-1,0
       0      .1       0     220     .08       0  366.58      .1       0
   369.2    .045       0   402.9      .1       0
#XS Ineff= 2 , 0
          275.31 2901.07
Permanent Ineff=
       F       F
Bank Sta=369.2,402.9
XS Rating Curve= 0 ,0
Exp/Cntr(USF)=0,0
Exp/Cntr=0.3,0.1

Type RM Length L Ch R = 1 ,13225   ,286.3,286,281.7
XS GIS Cut Line= 4
2308976.26369093 581322.65459751 2308677.5553471 581458.29256996
 2308612.7844052581473.5327915832308497.72073194581548.209877539
#Sta/Elev= 30
       0  2909.5    29.2 2907.11    39.6 2905.41    52.8 2906.36    92.6  2902.8
   137.9 2902.43   153.9 2901.15   165.1 2901.31   201.4 2899.93   213.5 2898.07
   246.1 2897.53   276.9  2894.9   303.2 2896.89   316.4 2897.15   337.7 2896.84
   347.5 2894.98   361.5  2894.4   378.2 2894.95   391.5  2896.2   395.3 2898.37
     415 2913.99   423.3  2918.9   428.7 2920.85   449.7 2925.35   462.1  2929.3
   471.6 2929.95   490.7  2935.5   500.2 2936.83   519.1 2941.85   531.8 2943.81
#Mann= 5 ,-1,0
       0      .1       0     190     .08       0   347.5    .045       0
   378.2     .08       0   404.6      .1       0
#XS Ineff= 2 , 0
          249.17 2906.21
Permanent Ineff=
       F       F
Bank Sta=347.5,378.2
XS Rating Curve= 0 ,0
Exp/Cntr(USF)=0,0
Exp/Cntr=0.3,0.1

Type RM Length L Ch R = 1 ,12939   ,212.8,212.2,207.5
XS GIS Cut Line= 3
2308938.75581215581095.4059595232308625.85861949581175.034410485
2308394.53201285581278.045429257
#Sta/Elev= 30
       0 2911.04      15 2908.68    72.7 2904.25    85.2 2903.94   118.2 2900.91
   135.2 2898.49   151.3 2897.69   163.6 2896.04     176 2895.43   192.5 2896.37
   225.5 2892.84   266.8 2892.34   319.4  2893.5   329.1 2892.91   343.9 2893.18
     386 2893.52   399.2 2892.68   407.9 2893.47   431.8  2892.4   448.82893.063
   464.1 2894.03   469.2 2894.27   473.6 2895.38   482.3 2904.74   495.4 2915.61
     513 2925.57   530.5 2937.84     548 2945.94   564.1 2956.53   576.1 2962.24
#Mann= 5 ,-1,0
       0      .1       0   343.9     .07       0   448.8    .045       0
   464.1     .07       0   564.1      .1       0
#XS Ineff= 2 , 0
          247.18 2900.06
Permanent Ineff=
       F       F
Bank Sta=448.8,464.1
XS Rating Curve= 0 ,0
Exp/Cntr(USF)=0,0
Exp/Cntr=0.3,0.1

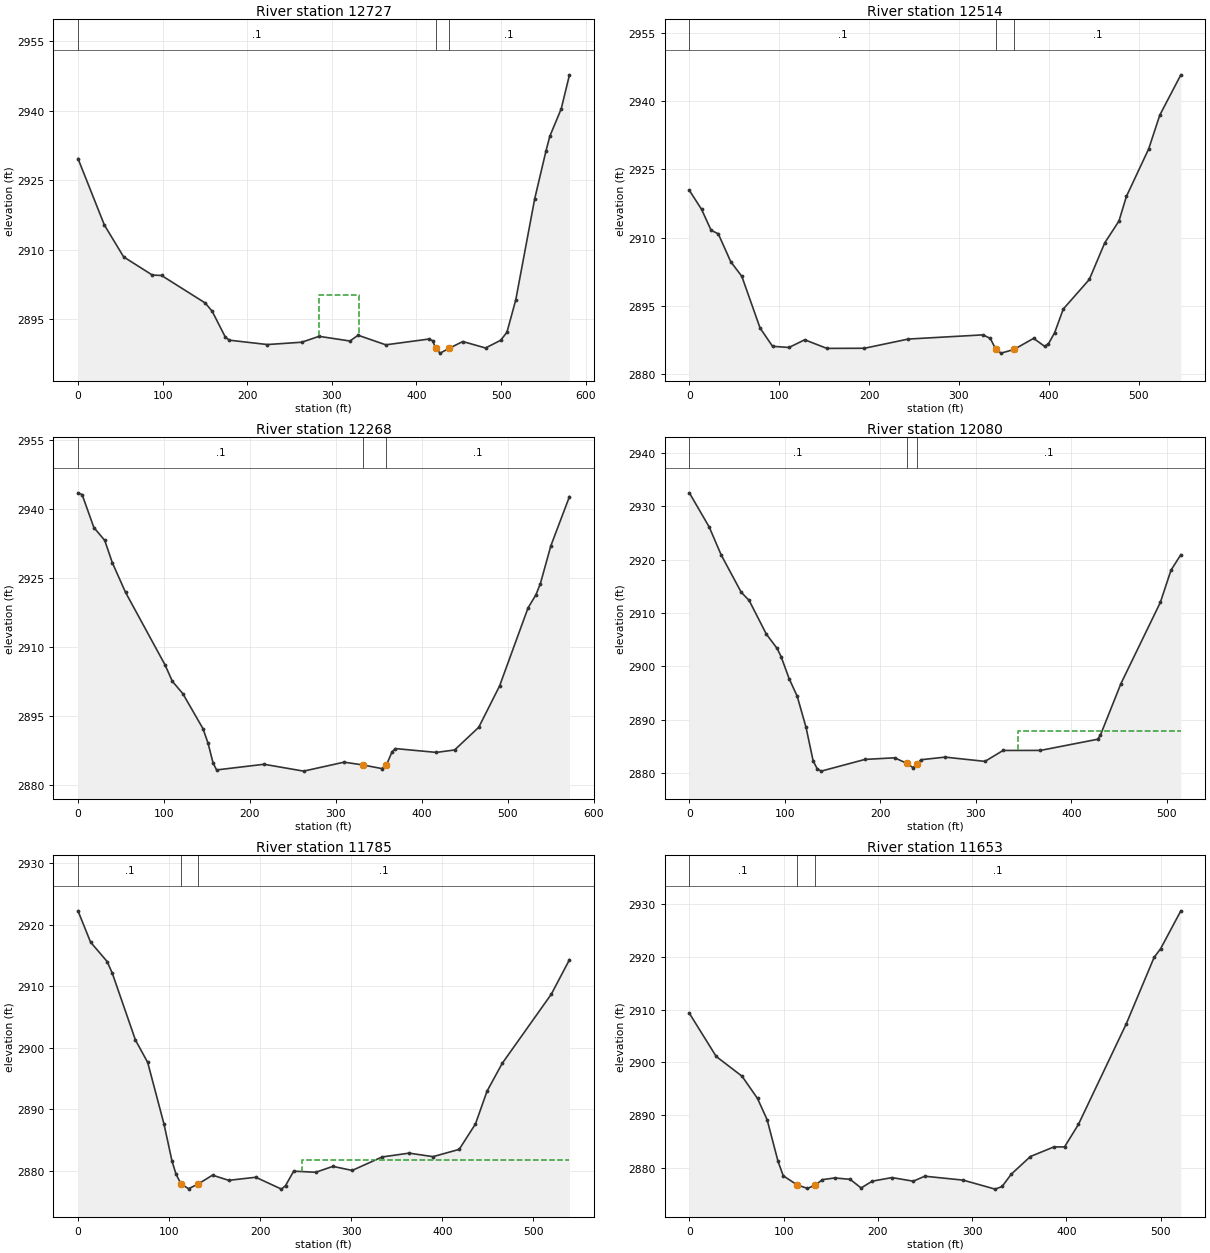
Type RM Length L Ch R = 1 ,12727   ,200.4,212.9,217.1
XS GIS Cut Line= 4
2308862.04669665580884.0748863412308743.65951617580963.932704317
2308559.93017771 580999.493221442308335.41237165581111.577528023
#Sta/Elev= 30
       0 2929.68    31.2 2915.35      54 2908.48    87.8 2904.58    98.8 2904.48
   150.4 2898.55   158.6 2896.77   174.1 2891.22   178.9 2890.54   223.8  2889.6
   264.5  2890.1   284.9 2891.37   321.5 2890.36     331 2891.61   363.8 2889.54
   414.6 2890.78   419.1 2890.45   422.72888.848     428 2887.75   438.4 2888.76
   454.8 2890.25   481.7 2888.86   499.6 2890.52     507 2892.26   517.4 2899.21
   539.8 2921.01   553.2 2931.37   557.7 2934.51   571.1 2940.37   580.9 2947.72
#Mann= 3 ,-1,0
       0      .1       0   422.7    .045       0   438.4      .1       0
#XS Ineff= 1 ,-1
  285.05  331.89 2900.35
Permanent Ineff=
       F
Bank Sta=422.7,438.4
XS Rating Curve= 0 ,0
Exp/Cntr(USF)=0,0
Exp/Cntr=0.3,0.1

Type RM Length L Ch R = 1 ,12514   ,244,246.2,248.9
XS GIS Cut Line= 4
2308711.84584576580732.8580206762308445.90397842580890.594314481
2308371.22689247 580896.690403132308213.49059866580937.839001514
#Sta/Elev= 30
       0  2920.4    13.6 2916.23    24.2 2911.64    32.2 2910.86    46.1 2904.73
    58.4 2901.53    78.7 2890.19    92.6 2886.17   110.9 2885.91   128.4  2887.6
   153.1 2885.71   194.9 2885.74   243.7 2887.76     327 2888.68     335 2887.89
     341 2885.57   347.1 2884.67   361.4 2885.48   383.2 2887.91   395.5 2886.16
   399.7 2886.69   406.7 2889.19   416.2 2894.34   445.2 2900.84   462.4 2908.88
   478.2 2913.66   486.5 2919.07   511.3  2929.5   523.7 2936.93   547.1 2945.76
#Mann= 3 ,-1,0
       0      .1       0     341    .045       0   361.4      .1       0
Bank Sta=341,361.4
XS Rating Curve= 0 ,0
Exp/Cntr(USF)=0,0
Exp/Cntr=0.3,0.1

Type RM Length L Ch R = 1 ,12268   ,192,188,183.1
XS GIS Cut Line= 4
2308640.21680412 580534.735139572308366.65482598580690.947411211
2308298.83583976580692.4714333742308139.57552379580794.580918252
#Sta/Elev= 30
       0 2943.58     4.8  2943.2    18.5 2936.03    31.1 2933.25    39.9 2928.42
    55.3 2921.96   101.4 2906.15   109.8 2902.62     122 2899.94   145.5 2892.31
   151.4 2889.14   157.2 2884.87   161.3 2883.35   216.5 2884.58   262.6 2883.09
   309.7 2885.04   331.4 2884.44   353.5 2883.65   358.8 2884.35   365.5 2887.29
   369.5 2887.99   417.1 2887.16   438.3 2887.69   466.4 2892.62   490.6 2901.58
   523.8 2918.58     533 2921.43   538.1 2923.83   550.3 2932.06     572 2942.77
#Mann= 3 ,-1,0
       0      .1       0   331.4    .045       0   358.8      .1       0
Bank Sta=331.4,358.8
XS Rating Curve= 0 ,0
Exp/Cntr(USF)=0,0
Exp/Cntr=0.3,0.1

Type RM Length L Ch R = 1 ,12080   ,297.3,294.8,289.5
XS GIS Cut Line= 3
 2308548.0134633580440.2457655032308227.20679813580539.307206057
2308086.99675919580650.560823909
#Sta/Elev= 30
       0 2932.56    20.8 2926.14    33.3 2920.91    54.3  2913.9    62.6 2912.36
    80.6 2906.04    91.9 2903.35    96.1  2901.8   104.5 2897.67   112.9 2894.39
   122.2 2888.53   129.6 2882.26   133.8 2880.78     138 2880.31     184 2882.51
   214.9 2882.81   227.7 2881.78   234.3 2880.95   238.5 2881.73   242.6 2882.45
   267.8 2882.94   309.6 2882.14   328.5 2884.19   367.7  2884.2   427.5 2886.29
   430.4 2887.04     452 2896.76   493.2 2911.98   504.4 2918.04   514.7 2920.95
#Mann= 3 ,-1,0
       0      .1       0   227.7    .045       0   238.5      .1       0
#XS Ineff= 2 , 0
                          344.11         2887.84
Permanent Ineff=
       F       F
Bank Sta=227.7,238.5
XS Rating Curve= 0 ,0
Exp/Cntr(USF)=0,0
Exp/Cntr=0.3,0.1

Type RM Length L Ch R = 1 ,11785   ,140.8,131.8,126.6
XS GIS Cut Line= 5
2308412.90733636580207.5026769542308193.48243548580314.715350045
2308167.92915588580343.0461600322308144.04239452580442.481748028
2308029.05263633580546.361384649
#Sta/Elev= 30
       0 2922.27    13.8 2917.18      32 2914.03    37.7 2912.11    63.1 2901.26
    76.5 2897.64    94.5 2887.56   103.2  2881.6   107.7 2879.43   113.2 2877.86
   121.4  2877.1   131.4 2877.82   147.7  2879.3   165.5 2878.46   195.2 2878.96
   223.4 2877.03   227.9 2877.61   236.8 2879.95     261 2879.77   279.9 2880.73
     301 2880.07   333.9 2882.26   363.5 2882.88   389.8 2882.31   418.5 2883.49
   436.4 2887.63   449.1 2892.96   465.7 2897.46   519.6 2908.71   539.6 2914.33
#Mann= 3 ,-1,0
       0      .1       0   113.2    .045       0   131.4      .1       0
#XS Ineff= 2 , 0
                           246.3         2881.69
Permanent Ineff=
       F       F
Bank Sta=113.2,131.4
XS Rating Curve= 0 ,0
Exp/Cntr(USF)=0,0
Exp/Cntr=0.3,0.1

Type RM Length L Ch R = 1 ,11653   ,391.2,392.7,404.8
XS GIS Cut Line= 3
2308312.36073621580060.2935662352308177.37275921580205.280652642
2307949.05976108580434.149156855
#Sta/Elev= 30
       0 2909.33    28.5 2901.13    55.9 2897.38    72.3 2893.16    82.5 2889.13
    94.1 2881.21    99.6 2878.49     114 2876.79   125.3 2876.08   133.8 2876.75
   141.2 2877.75   154.2 2878.07   170.6 2877.81   182.2 2876.17     194 2877.46
   214.9 2878.14   237.5 2877.46   249.8  2878.4   290.4 2877.66   324.4 2875.95
   331.8 2876.45   341.4 2878.77   361.8 2882.14   386.7 2883.96     398 2883.96
   412.7 2888.22   463.5 2907.32     493 2919.92     500  2921.6   521.4 2928.77
#Mann= 3 ,-1,0
       0      .1       0     114    .045       0   133.8      .1       0
Bank Sta=114,133.8
XS Rating Curve= 0 ,0
Exp/Cntr(USF)=0,0
Exp/Cntr=0.3,0.1