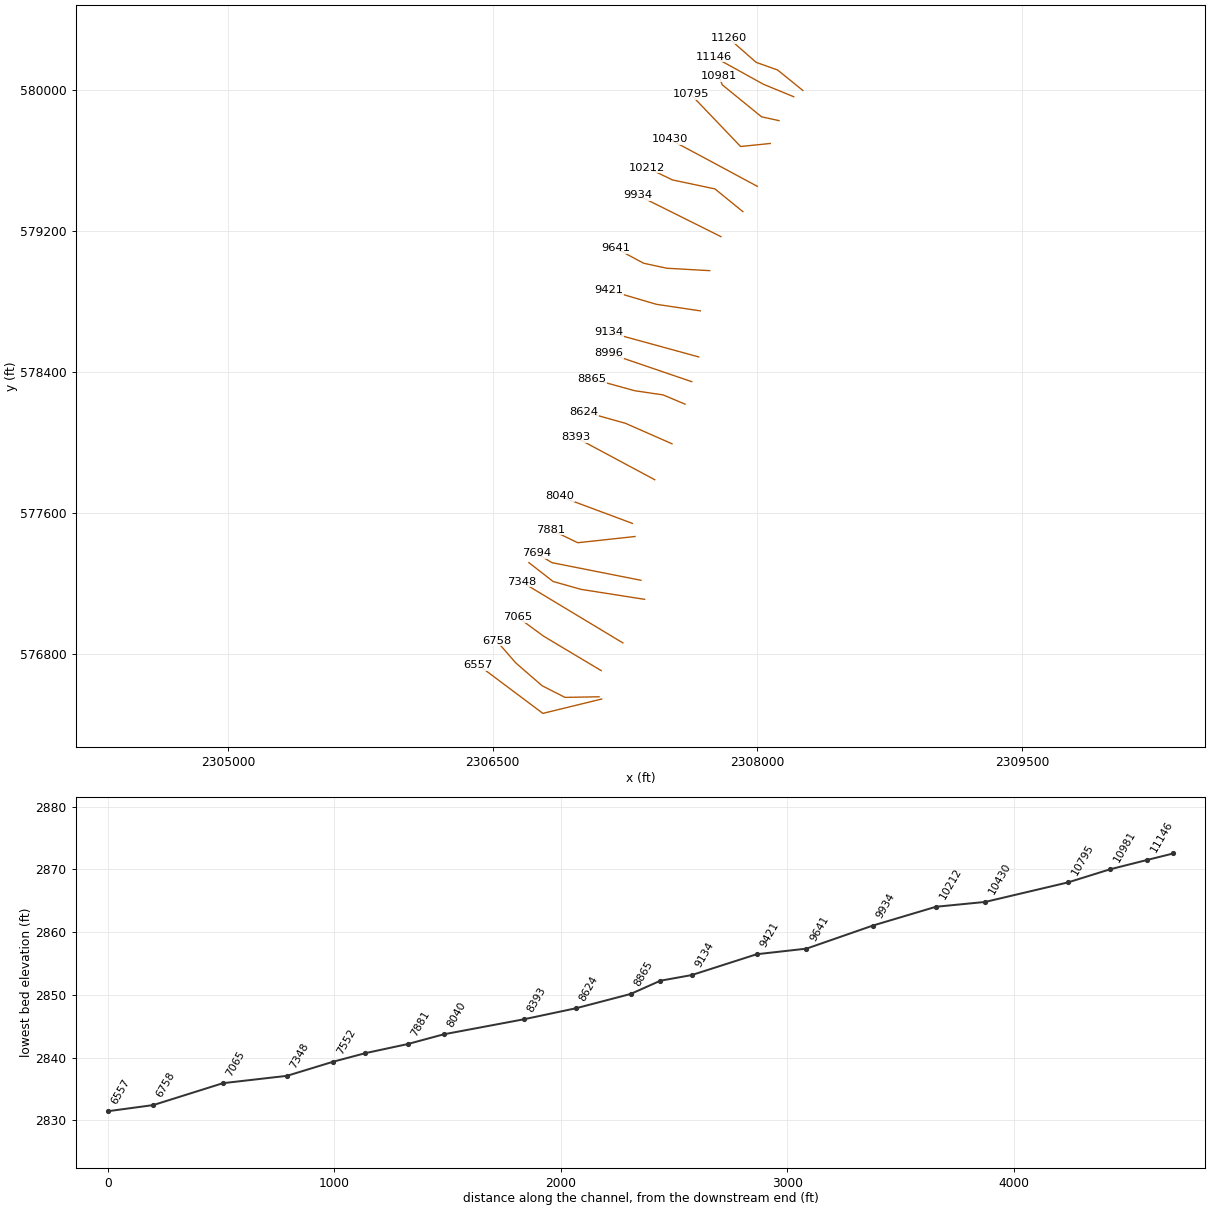
HEC-RAS study MNTNLCKCK.prj: MNTNLCKCK

--- MNTNLCKCK.g01 (geometry) --- (continued)

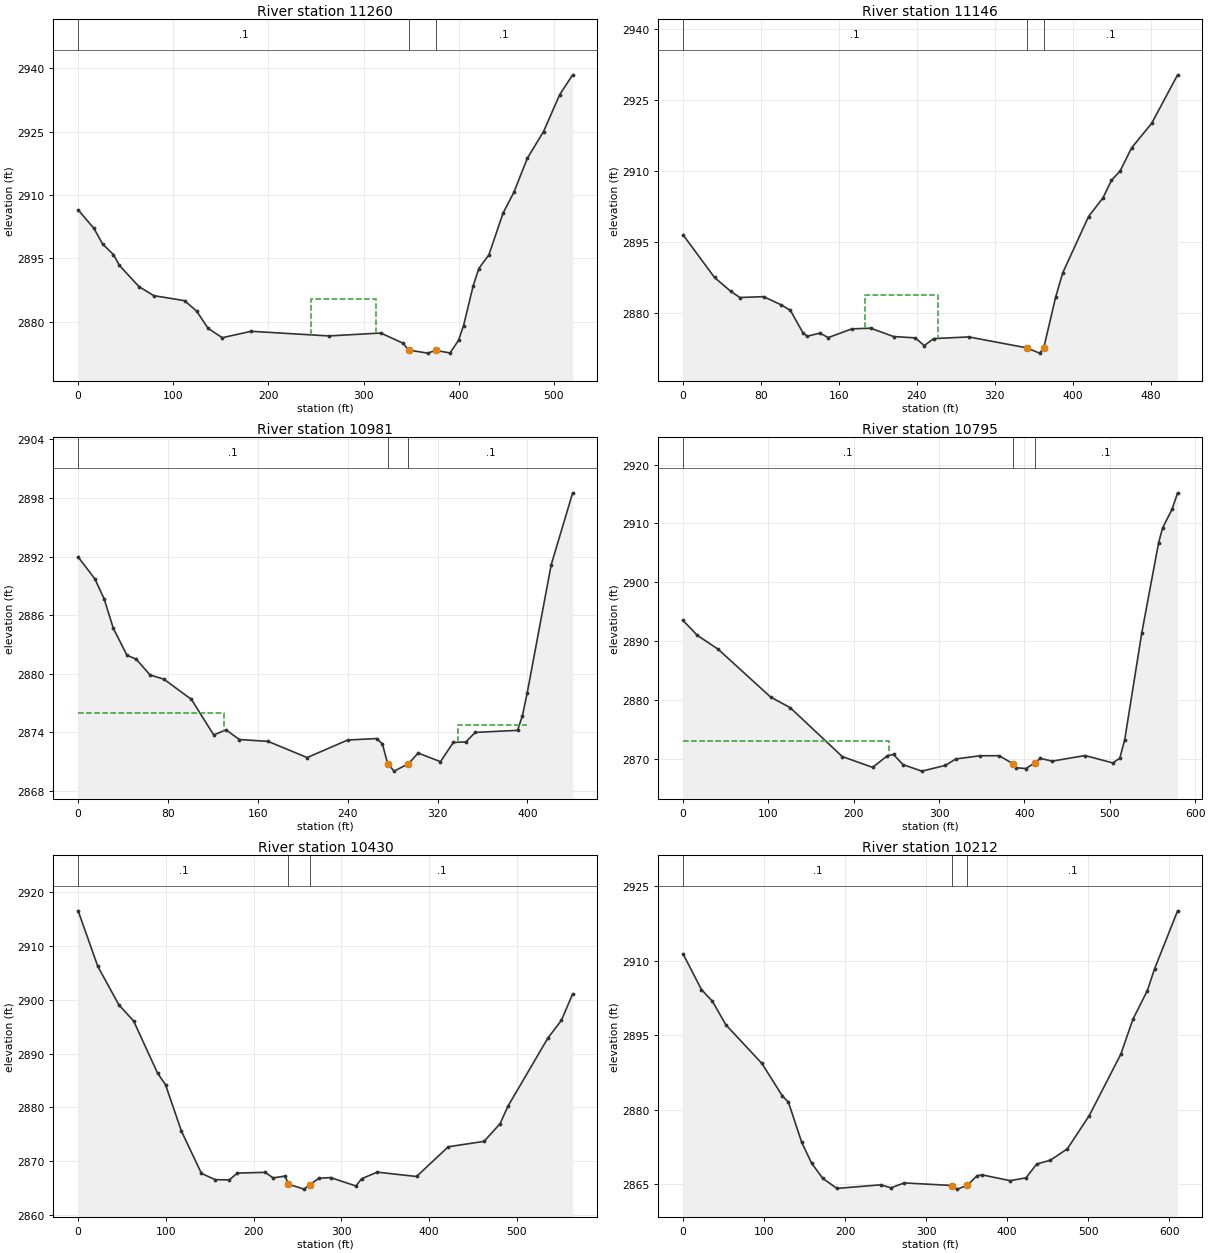
Type RM Length L Ch R = 1 ,11260   ,110.3,114.6,114.3
XS GIS Cut Line= 4
2308257.92114055579994.7438490092308114.60057238 580110.84461935
2307992.94474125580154.1740934492307837.95854544580290.273082605
#Sta/Elev= 30
       0 2906.46    16.6 2902.06    25.7 2898.37    37.1 2895.87    43.4 2893.29
      64 2888.26    79.5 2886.14   111.9 2884.95   124.6 2882.46   136.6 2878.39
   151.5 2876.18   181.8  2877.7   263.5  2876.6   318.1 2877.29   341.2 2874.91
   347.4 2873.26   367.3 2872.53   375.8 2873.18   390.9 2872.57   399.8 2875.56
   405.1 2879.04   415.1 2888.36   421.1 2892.56   431.7 2895.78   446.6 2905.67
     458 2910.61   472.2  2918.7   489.2    2925   506.1  2933.7   519.8 2938.42
#Mann= 3 ,-1,0
       0      .1       0   347.4    .045       0   375.8      .1       0
#XS Ineff= 1 ,-1
  245.18  312.96  2885.3
Permanent Ineff=
       F
Bank Sta=347.4,375.8
XS Rating Curve= 0 ,0
Exp/Cntr(USF)=0,0
Exp/Cntr=0.3,0.1

Type RM Length L Ch R = 1 ,11146   ,167.6,165.1,160.3
XS GIS Cut Line= 3
2308206.04803643579959.2704671522308034.64964596580029.804498858
2307752.47389455580185.734064389
#Sta/Elev= 30
       0 2896.53    32.3 2887.51    48.9 2884.59    58.3 2883.27    82.6 2883.45
     101 2881.69   110.2 2880.53   123.1  2875.8   127.5 2875.08   140.4 2875.73
   149.1 2874.79   173.2 2876.63   192.6 2876.78   216.1 2875.01   238.4 2874.73
   247.6 2873.09   257.3 2874.57   293.3 2874.93   352.7 2872.62     366  2871.5
   370.32872.623   382.5 2883.35   389.8  2888.5   416.3 2900.41     431 2904.33
   439.8 2908.05   448.7 2910.06   460.5 2914.94   481.1 2920.13   507.7 2930.39
#Mann= 3 ,-1,0
       0      .1       0   352.7    .045       0   370.3      .1       0
#XS Ineff= 1 ,-1
  186.38  262.13 2883.86
Permanent Ineff=
       F
Bank Sta=352.7,370.3
XS Rating Curve= 0 ,0
Exp/Cntr(USF)=0,0
Exp/Cntr=0.3,0.1

Type RM Length L Ch R = 1 ,10981   ,186.9,185.9,184.8
XS GIS Cut Line= 4
2308122.69164427579823.6469729122308023.68817621579845.489224202
 2307800.8338358580026.8575600632307782.14493101580074.923483894
#Sta/Elev= 30
       0 2891.95    14.9 2889.71    23.1 2887.67    31.3 2884.65    43.5 2881.87
    51.7 2881.48      64 2879.86    76.3 2879.43   100.9 2877.35   120.7 2873.71
   131.7 2874.23   143.5 2873.24   169.1 2873.05   203.9 2871.39     240 2873.19
   265.8 2873.34   270.9 2872.78  275.55 2870.78   281.3    2870   294.1 2870.76
   302.7 2871.85   322.6 2870.97     334 2872.94   345.3    2873   353.5 2873.97
   391.2 2874.18   395.5 2875.65   399.8 2878.01   421.2 2891.17   440.3 2898.53
#Mann= 3 ,-1,0
       0      .1       0  275.55    .045       0   294.1      .1       0
#XS Ineff= 2 ,-1
       0  130.282875.925   337.8     400 2874.75
Permanent Ineff=
       F       F
Bank Sta=275.55,294.1
XS Rating Curve= 0 ,0
Exp/Cntr(USF)=0,0
Exp/Cntr=0.3,0.1

Type RM Length L Ch R = 1 ,10795   ,356.8,365.2,374.5
XS GIS Cut Line= 3
2308072.99949953579694.3021136332307904.85653319579677.053356058
2307621.30738012579973.907534036
#Sta/Elev= 30
       0 2893.51    16.9 2890.96      41 2888.64   102.7 2880.48   125.5  2878.7
   186.6 2870.38   222.1 2868.55   239.5 2870.53   246.6 2870.74   257.7 2869.02
   279.8 2867.91   307.5 2868.89   319.5 2869.97   347.8 2870.52   370.5 2870.53
   386.42869.178   390.1 2868.49   401.7 2868.35   412.1 2869.31   418.6 2870.07
   432.7 2869.61   471.1 2870.56   503.4 2869.31   511.7 2870.09   517.5 2873.21
   537.4  2891.3   557.2 2906.69   561.9 2909.23     573 2912.41   579.5  2915.2
#Mann= 3 ,-1,0
       0      .1       0   386.4    .045       0   412.1      .1       0
#XS Ineff= 2 , 0
           241.2 2873.06
Permanent Ineff=
       F       F
Bank Sta=386.4,412.1
XS Rating Curve= 0 ,0
Exp/Cntr(USF)=0,0
Exp/Cntr=0.3,0.1

Type RM Length L Ch R = 1 ,10430   ,211.2,217.4,219.4
XS GIS Cut Line= 3
2307999.90709284 579451.215280662307702.85691257579610.985994735
2307503.07102122579717.581284388
#Sta/Elev= 30
       0 2916.58    22.4 2906.25    46.4 2899.09    63.3 2896.07    90.5 2886.39
    99.6 2884.22   117.8 2875.57   140.5 2867.74   156.1 2866.56   172.3 2866.52
   181.5 2867.79   213.2 2867.92   222.2 2866.89   235.9 2867.23   239.7 2865.72
   257.5  2864.8   264.1 2865.63   274.4 2866.81   287.7 2866.95   316.6 2865.39
   323.2 2866.74   340.9 2867.96   385.7 2867.15   421.9 2872.68   462.7 2873.69
   480.9 2876.97   489.9 2880.22   535.3 2892.87   550.8  2896.2   563.7 2901.12
#Mann= 3 ,-1,0
       0      .1       0   239.7    .045       0   264.1      .1       0
Bank Sta=239.7,264.1
XS Rating Curve= 0 ,0
Exp/Cntr(USF)=0,0
Exp/Cntr=0.3,0.1

Type RM Length L Ch R = 1 ,10212   ,279,278.3,273.4
XS GIS Cut Line= 4
2307917.83029917 579307.897298872307759.33199428579436.677171589
2307518.53649263579487.7319140282307374.51639829579557.074922416
#Sta/Elev= 30
       0 2911.37    22.7 2904.19    36.2 2901.84    52.8  2897.1    97.2 2889.34
   122.6 2882.77     130 2881.53   146.4 2873.45   158.5 2869.29   172.2 2866.22
   189.8 2864.17     244  2864.9   256.5 2864.29   272.9 2865.28   332.1 2864.76
   338.3 2864.03   350.6 2864.79   362.8 2866.73   369.2 2866.89   403.7 2865.73
   423.2 2866.31   436.4 2869.09   453.2 2869.84   474.2 2872.15   501.2 2878.83
   540.1 2891.18   555.1 2898.23   572.9    2904   581.7 2908.33   610.2 2920.04
#Mann= 3 ,-1,0
       0      .1       0   332.1    .045       0   350.6      .1       0
Bank Sta=332.1,350.6
XS Rating Curve= 0 ,0
Exp/Cntr(USF)=0,0
Exp/Cntr=0.3,0.1

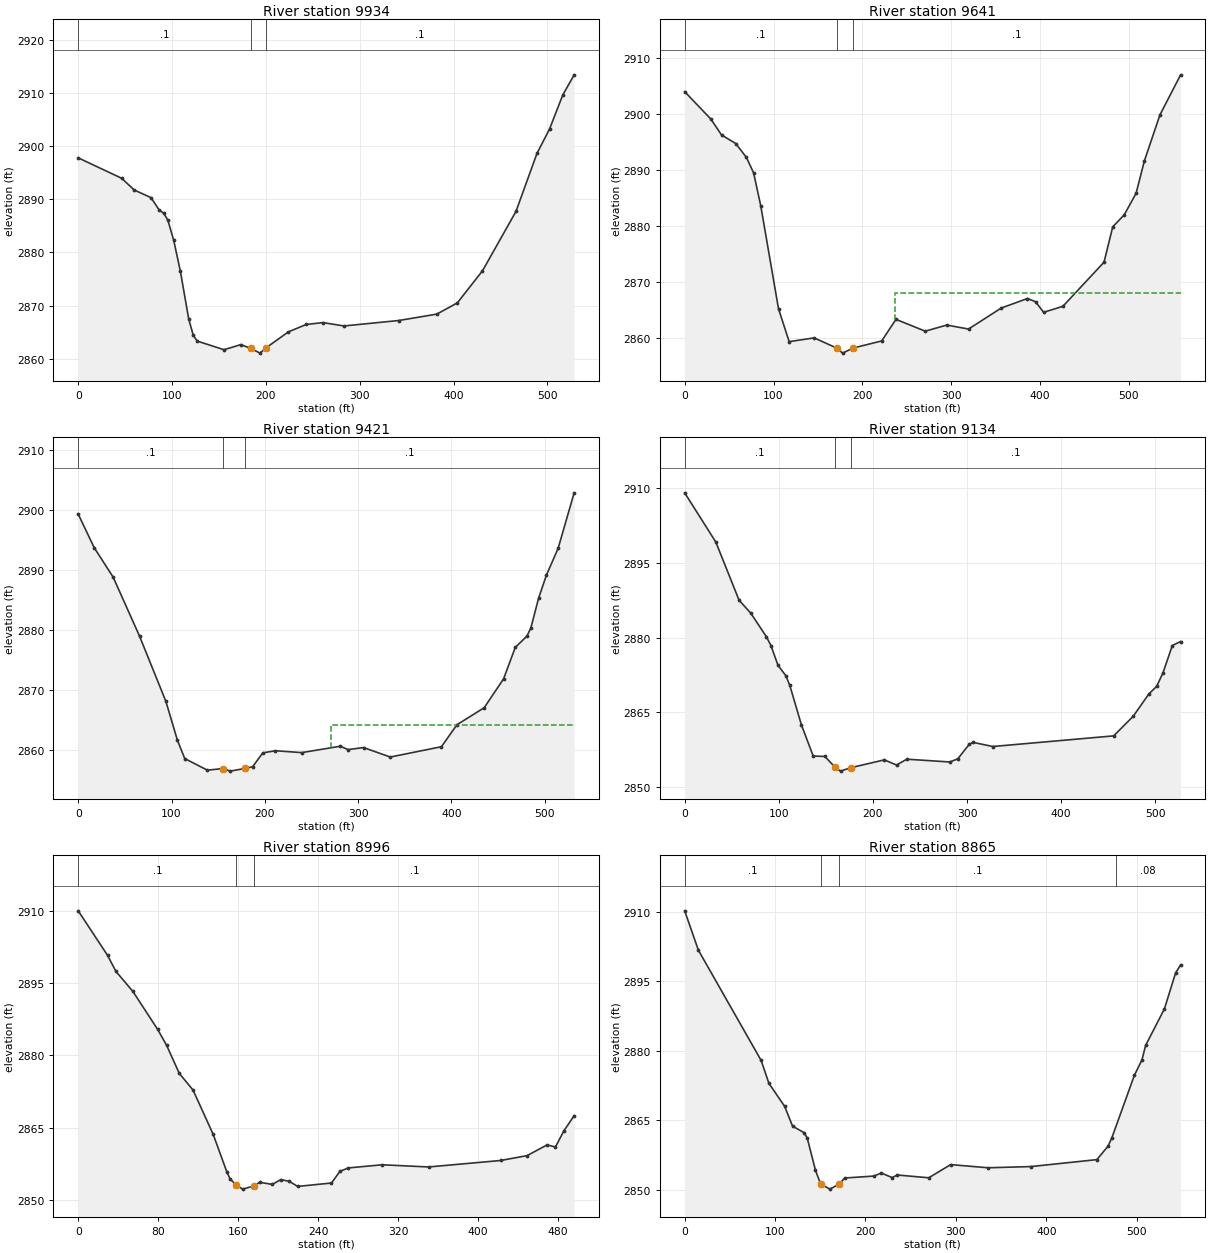
Type RM Length L Ch R = 1 ,9934    ,283.3,293.1,299.3
XS GIS Cut Line= 2
2307793.62249293579166.1632377712307320.70469976579401.886793667
#Sta/Elev= 30
       0 2897.83    46.3 2893.98    59.7 2891.77    77.6 2890.33    86.5 2887.94
      91 2887.42    95.5  2886.1   101.8 2882.26   108.9 2876.42   117.8 2867.41
   122.6 2864.39   126.8 2863.31   155.4 2861.68   173.3 2862.65   183.6 2861.94
   193.8 2861.04   200.2 2862.05     224 2865.05     243 2866.44   260.8 2866.79
   283.2 2866.16   341.3 2867.18   382.1 2868.39   403.9  2870.5   430.7 2876.54
   466.4 2887.73   488.8 2898.67   502.2 2903.27   516.3 2909.68   528.4 2913.47
#Mann= 3 ,-1,0
       0      .1       0   183.6    .045       0   200.2      .1       0
Bank Sta=183.6,200.2
XS Rating Curve= 0 ,0
Exp/Cntr(USF)=0,0
Exp/Cntr=0.3,0.1

Type RM Length L Ch R = 1 ,9641    ,220.7,219.6,217.6
XS GIS Cut Line= 4
2307729.61356212578973.3744342322307486.53202722578987.090633693
2307355.46612126579015.2850436972307196.20580529579100.630284789
#Sta/Elev= 30
       0 2904.05    29.5 2899.14    41.5 2896.31    57.5 2894.78    69.5  2892.3
    77.6 2889.53    85.6 2883.69   105.6 2865.29   117.6 2859.41   145.7 2860.08
   171.6 2858.23   177.7 2857.36   189.7 2858.27   221.8 2859.54   237.8 2863.39
   270.8 2861.28     295 2862.37   319.5 2861.66   356.3 2865.41   385.8 2867.11
   394.9 2866.54     404 2864.65   425.7 2865.72     472  2873.6   481.8 2879.92
   494.7 2882.04   508.1 2885.91   517.4 2891.68     535 2899.93   558.2 2907.05
#Mann= 3 ,-1,0
       0      .1       0   171.6    .045       0   189.7      .1       0
#XS Ineff= 2 , 0
                          236.96         2868.17
Permanent Ineff=
       F       F
Bank Sta=171.6,189.7
XS Rating Curve= 0 ,0
Exp/Cntr(USF)=0,0
Exp/Cntr=0.3,0.1

Type RM Length L Ch R = 1 ,9421    ,281.6,287,281.2
XS GIS Cut Line= 3
2307677.16891146578745.3616684662307428.01414825578782.543237161
2307159.62927339578861.358805299
#Sta/Elev= 30
       0 2899.34    17.2 2893.72    37.4 2888.84    65.7    2879      94 2868.09
   106.3 2861.64   114.2 2858.56   138.5 2856.63   155.72856.907   162.8 2856.47
     179 2856.92     187 2857.21   197.8 2859.51   211.3 2859.87   239.6 2859.56
   280.9 2860.62   289.3 2860.06   305.9  2860.4   334.5 2858.82   389.3 2860.54
     406 2864.21   435.2 2867.05     456 2871.88   468.5 2877.11     481 2878.99
   485.2 2880.35   493.5 2885.32   501.9 2889.17   514.4 2893.62   531.6 2902.89
#Mann= 3 ,-1,0
       0      .1       0   155.7    .045       0     179      .1       0
#XS Ineff= 2 , 0
                          271.44         2864.17
Permanent Ineff=
       F       F
Bank Sta=155.7,179
XS Rating Curve= 0 ,0
Exp/Cntr(USF)=0,0
Exp/Cntr=0.3,0.1

Type RM Length L Ch R = 1 ,9134    ,139.3,138.3,136.9
XS GIS Cut Line= 2
2307667.87896933578484.2506806222307159.61757818578623.656578533
#Sta/Elev= 30
       0 2909.11    33.1 2899.21    57.8 2887.52    70.2 2884.92    86.8 2880.19
    91.7 2878.38    99.2 2874.41   107.5 2872.34   111.7 2870.39   124.1 2862.42
   136.6 2856.18     149  2856.1     160 2853.89   165.6 2853.15   176.3 2853.83
   212.1 2855.41   225.1 2854.38   236.1 2855.55   281.7 2854.99   290.2 2855.62
   302.5 2858.58   306.6 2858.93   327.4  2858.1   455.9 2860.24   476.7  2864.2
   493.3 2868.68   501.6 2870.21   508.3 2872.94   518.2 2878.41     527 2879.21
#Mann= 3 ,-1,0
       0      .1       0     160    .045       0   176.3      .1       0
Bank Sta=160,176.3
XS Rating Curve= 0 ,0
Exp/Cntr(USF)=0,0
Exp/Cntr=0.3,0.1

Type RM Length L Ch R = 1 ,8996    ,126.6,131.1,133.7
XS GIS Cut Line= 2
2307627.88010636578344.0486232252307158.49213252578504.398552178
#Sta/Elev= 30
       0 2909.99    29.3 2900.77    37.7 2897.43    54.6 2893.29    79.4 2885.41
    88.5 2882.05   101.1 2876.26   114.9 2872.79     135  2863.6   148.7  2855.8
   151.9 2854.37   158.32853.039   164.5 2852.25   176.32852.939   181.4 2853.67
   194.1 2853.23   202.6 2854.22     211 2853.88   219.5 2852.81   253.3 2853.52
   261.8 2855.95   270.2 2856.65     304  2857.3   350.5 2856.85   422.4 2858.19
   448.9  2859.2   468.9 2861.42   477.3    2861   485.8 2864.37     496 2867.49
#Mann= 3 ,-1,0
       0      .1       0   158.3    .045       0   176.3      .1       0
Bank Sta=158.3,176.3
XS Rating Curve= 0 ,0
Exp/Cntr(USF)=0,0
Exp/Cntr=0.3,0.1

Type RM Length L Ch R = 1 ,8865    ,248.2,240.6,237.1
XS GIS Cut Line= 4
2307590.16553426 578216.69743062 2307464.6584609 578269.34197016
2307305.46447814578292.6013544172307062.89120462578359.437346348
#Sta/Elev= 30
       0 2910.21    15.2  2901.7    84.6 2877.91    93.2 2872.97   110.6    2868
   119.3 2863.74   132.3  2862.3   135.7 2861.07   144.7 2854.19   150.5 2851.21
   160.8 2850.14     171 2851.26     177 2852.54   209.4 2852.96   217.4 2853.62
   229.6 2852.63   235.1 2853.19     270 2852.59   294.2 2855.43   335.7 2854.75
   383.1 2855.01     456 2856.51   468.4 2859.44   472.6 2861.25   497.5 2874.73
   505.8 2878.02   509.9 2881.16   530.7 2889.06   543.1 2896.84   548.6 2898.54
#Mann= 4 ,-1,0
       0      .1       0   150.5    .045       0     171      .1       0
  476.99     .08       0
Bank Sta=150.5,171
XS Rating Curve= 0 ,0
Exp/Cntr(USF)=0,0
Exp/Cntr=0.3,0.1

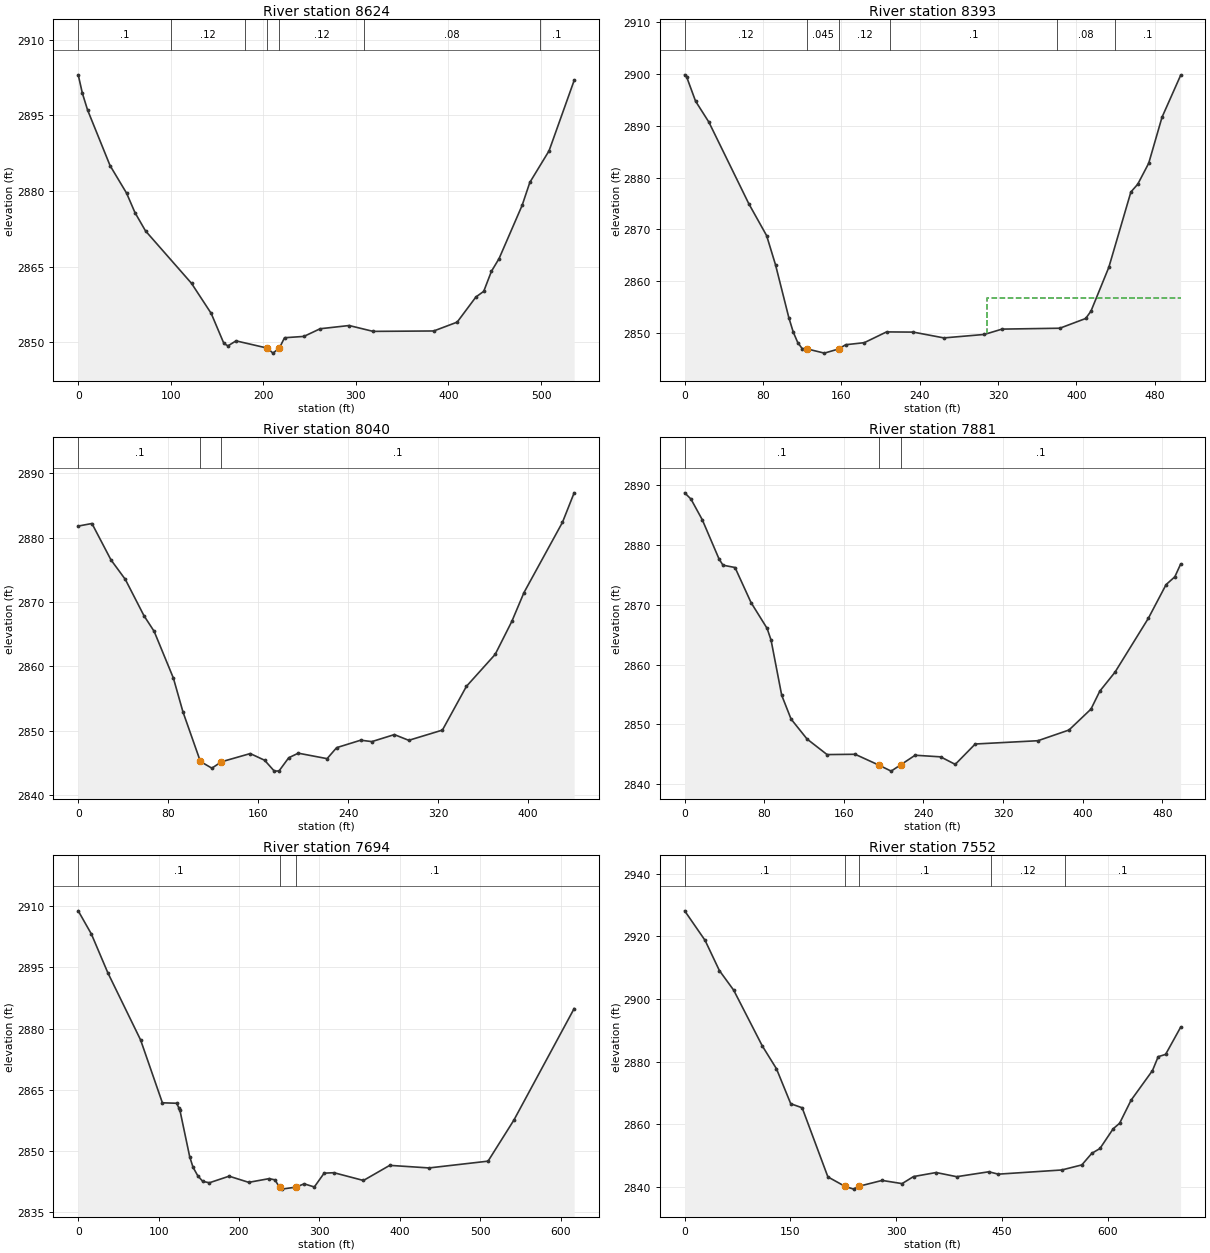
Type RM Length L Ch R = 1 ,8624    ,234.1,231.6,223.3
XS GIS Cut Line= 3
2307516.25045939577991.9041616722307251.75412707578108.256395668
2307014.08515689578174.786821155
#Sta/Elev= 30
       0 2903.01     4.5 2899.36    10.1 2896.05    34.4 2885.03    52.3 2879.55
    61.3 2875.72    72.7 2872.09   122.4  2861.7   143.7 2855.73   157.4 2849.78
   161.8 2849.31   170.5  2850.3   204.4 2848.86   210.4 2847.87   217.32848.868
   222.9 2850.92   243.8 2851.18   261.4  2852.7   292.7 2853.34   318.6 2852.18
   384.1 2852.26   409.4 2854.01   429.7    2859   438.1 2860.11   446.4 2864.07
   454.7 2866.61   479.6 2877.15   487.9 2881.69   508.7 2887.96   535.8  2901.9
#Mann= 7 ,-1,0
       0      .1       0     100     .12       0     180      .1       0
   204.4    .045       0   217.3     .12       0  308.96     .08       0
  498.96      .1       0
Bank Sta=204.4,217.3
XS Rating Curve= 0 ,0
Exp/Cntr(USF)=0,0
Exp/Cntr=0.3,0.1

Type RM Length L Ch R = 1 ,8393    ,347.8,353.2,352.6
XS GIS Cut Line= 2
2307417.95102991577788.4472029972306971.41253634578027.718682488
#Sta/Elev= 30
       0 2899.86     1.9 2899.52    11.1 2894.78    24.7 2890.73    65.5 2874.96
    83.7  2868.8    92.8 2863.16   106.4 2852.95   110.9 2850.17   115.5 2848.14
     120 2846.98   124.5 2846.94   142.7  2846.1   157.4 2846.91   164.4 2847.72
   183.5 2848.12   206.2  2850.2   233.5 2850.16   264.8 2849.04   306.1 2849.71
   324.2 2850.74   383.2 2850.91   409.6 2852.79     415  2854.2   433.3  2862.7
   455.8 2877.23   462.8 2878.73     474 2882.78   487.6 2891.67   506.6 2899.76
#Mann= 6 ,-1,0
       0     .12       0   124.5    .045       0   157.4     .12       0
     210      .1       0     380     .08       0     440      .1       0
#XS Ineff= 2 , 0
                          308.97         2856.68
Permanent Ineff=
       F       F
Bank Sta=124.5,157.4
XS Rating Curve= 0 ,0
Exp/Cntr(USF)=0,0
Exp/Cntr=0.3,0.1

Type RM Length L Ch R = 1 ,8040    ,152.8,158.6,172.1
XS GIS Cut Line= 2
2307291.45719044577540.7936016142306878.44718444577694.719840012
#Sta/Elev= 30
       0 2881.81    12.2 2882.21    29.1 2876.56    41.9 2873.51    58.4 2867.89
    67.5 2865.44    84.6 2858.17    93.1 2852.92   108.6 2845.21   118.8 2844.17
   127.3 2845.16   152.9 2846.44   165.7  2845.4   174.3 2843.71   178.5 2843.74
   187.1 2845.79   195.6  2846.5   221.2 2845.65   229.7 2847.36   251.1 2848.52
     261  2848.3     281 2849.39   293.8  2848.5   323.7 2850.09     345 2856.88
   370.6 2861.86   385.4 2866.99   396.2 2871.47   430.4 2882.39   440.8 2886.98
#Mann= 3 ,-1,0
       0      .1       0   108.6    .045       0   127.3      .1       0
Bank Sta=108.6,127.3
XS Rating Curve= 0 ,0
Exp/Cntr(USF)=0,0
Exp/Cntr=0.3,0.1

Type RM Length L Ch R = 1 ,7881    ,192,187.2,178.9
XS GIS Cut Line= 3
2307306.45408818577466.4041069032306982.05623565577431.154245605
2306826.97622238577505.777775621
#Sta/Elev= 30
       0 2888.74     6.3  2887.7    17.7 2884.23    34.5 2877.68    38.5 2876.63
    50.6 2876.24    66.7 2870.37    82.8 2866.06    86.8  2864.1    97.5 2854.86
   106.9 2850.88     123 2847.53   143.1 2844.93   171.3 2844.98   195.5 2843.14
   207.5 2842.16   217.3 2843.24   231.6 2844.82   257.2 2844.55   271.9 2843.29
     292  2846.7     355 2847.25   386.2 2849.04   408.3 2852.54   417.2 2855.55
   432.5 2858.73     466 2867.75   483.8 2873.38   492.6 2874.69   498.4 2876.81
#Mann= 3 ,-1,0
       0      .1       0   195.5    .045       0   217.3      .1       0
Bank Sta=195.5,217.3
XS Rating Curve= 0 ,0
Exp/Cntr(USF)=0,0
Exp/Cntr=0.3,0.1

Type RM Length L Ch R = 1 ,7694    ,137.8,141.6,141.2
XS GIS Cut Line= 3
2307340.25925118577218.1903977832306835.83919104577318.082572614
 2306747.9907536577371.216708162
#Sta/Elev= 30
       0 2908.86    16.4 2903.17    36.8 2893.71    77.6 2877.24   104.7 2861.85
   122.4 2861.74   125.1 2860.66   126.5 2860.04   138.7 2848.63   142.8 2846.08
   148.8 2843.95     155  2842.6   163.2 2842.27   187.7 2843.88   212.1 2842.37
   237.5 2843.28   244.7 2842.98   250.5 2841.15   252.9 2840.71   270.9  2841.2
     281 2842.01   293.7 2841.24   305.9 2844.62   318.1 2844.73   354.8 2842.83
   387.5 2846.53   436.4  2845.9   509.8 2847.56   541.9  2857.6   616.9 2884.93
#Mann= 3 ,-1,0
       0      .1       0   250.5    .045       0   270.9      .1       0
Bank Sta=250.5,270.9
XS Rating Curve= 0 ,0
Exp/Cntr(USF)=0,0
Exp/Cntr=0.3,0.1

Type RM Length L Ch R = 1 ,7552    ,211.7,203.9,194
XS GIS Cut Line= 4
2307360.80019883577110.2573407472307001.13096851577166.646160754
2306841.87065254577211.6048145442306704.70865793577318.286365909
#Sta/Elev= 30
       0 2928.19      29 2918.73    49.2 2909.13    69.5 2902.86     110 2885.09
   130.2 2877.76   150.4 2866.61   166.6 2865.32   203.1 2843.25     2272840.274
   239.5 2839.35   246.9 2840.25     280 2842.13   308.3 2841.11   324.5 2843.36
   356.6 2844.65   385.8 2843.32   431.3 2844.89   444.7 2844.13   534.7 2845.46
   563.2 2847.08   577.3 2850.77   588.9 2852.32   607.7 2858.63   616.8 2860.38
     633 2867.72   663.4  2877.2   671.5 2881.63     682 2882.36   703.3 2891.03
#Mann= 5 ,-1,0
       0      .1       0     227    .045       0   246.9      .1       0
  434.06     .12       0  539.55      .1       0
Bank Sta=227,246.9
XS Rating Curve= 0 ,0
Exp/Cntr(USF)=0,0
Exp/Cntr=0.3,0.1

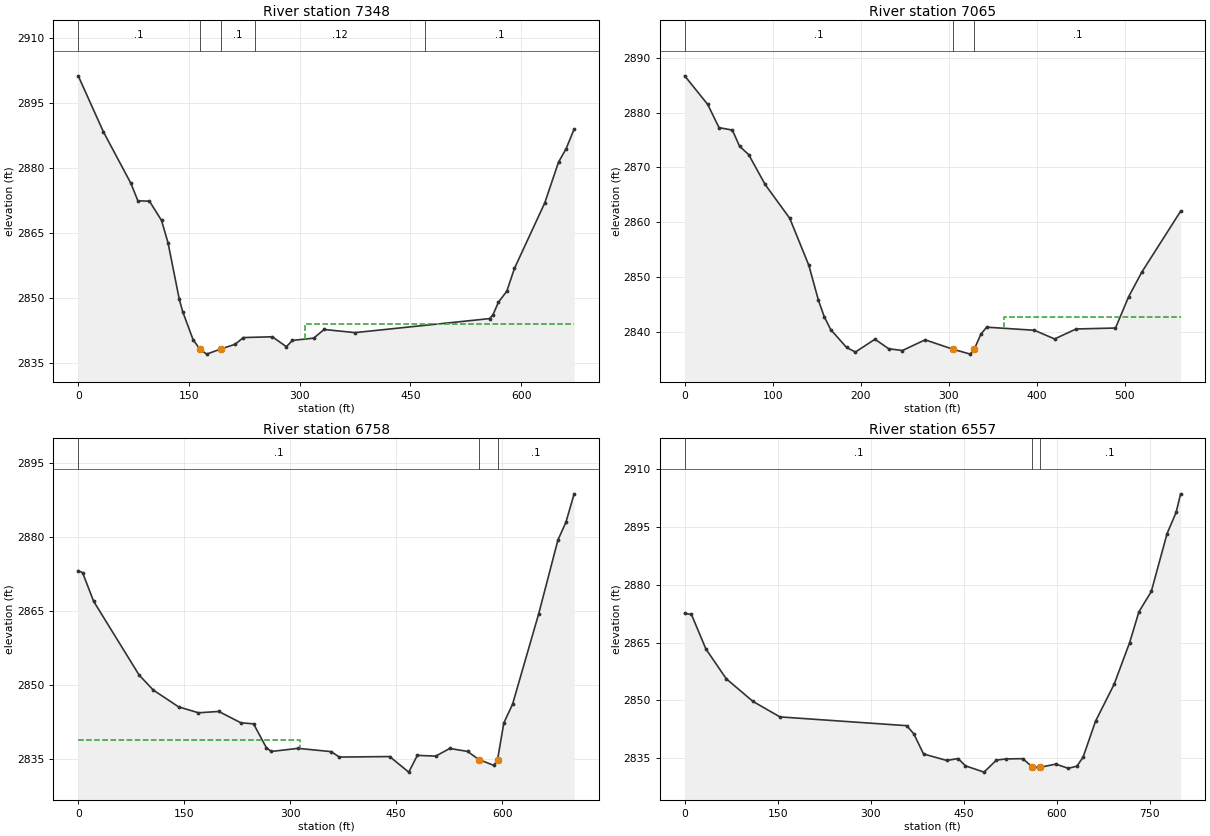
Type RM Length L Ch R = 1 ,7348    ,251.2,282.7,279.7
XS GIS Cut Line= 2
2307237.35440367576863.3657504452306662.03603738577210.080792382
#Sta/Elev= 30
       0 2901.26    34.1 2888.36    71.4 2876.45    80.8 2872.45    96.5 2872.36
   112.9 2867.91   121.7 2862.71   136.8 2849.83   141.5 2846.89   155.5 2840.47
   164.8 2838.23     174  2837.1   192.9 2838.27   212.7 2839.38   223.6 2840.92
   262.9  2841.1   281.9 2838.82   290.2 2840.26     319 2840.79     333 2842.78
     375 2842.06   557.1 2845.29   561.7 2846.17   569.2 2849.08   580.5 2851.61
   590.8 2856.85   631.9 2871.97   650.5 2881.34   660.8 2884.45   671.7    2889
#Mann= 5 ,-1,0
       0      .1       0   164.8    .045       0   192.9      .1       0
     240     .12       0     470      .1       0
#XS Ineff= 2 , 0
                          307.82         2844.11
Permanent Ineff=
       F       F
Bank Sta=164.8,192.9
XS Rating Curve= 0 ,0
Exp/Cntr(USF)=0,0
Exp/Cntr=0.3,0.1

Type RM Length L Ch R = 1 ,7065    ,326.3,307.7,296.4
XS GIS Cut Line= 3
2307114.66762495576706.2255545072306787.30050225 576901.92214305
2306640.46774495 577009.64753502
#Sta/Elev= 30
       0  2886.7    26.2 2881.48      39 2877.25    54.2  2876.8    62.3 2873.87
    72.8 2872.31    91.4 2866.88   119.4  2860.7   141.1 2852.12     152 2845.74
   158.6 2842.75     166 2840.39     184 2837.14     194 2836.31   216.2 2838.65
   231.8 2836.91   247.4 2836.59   273.2 2838.54   304.4 2836.85   324.5 2835.93
   329.1 2836.84   336.5 2839.56   343.1 2840.85   397.4 2840.28   420.3  2838.7
   444.8 2840.52   489.5 2840.69   504.3 2846.35   519.2 2850.84   563.5    2862
#Mann= 3 ,-1,0
       0      .1       0   304.4    .045       0   329.1      .1       0
#XS Ineff= 2 , 0
                          362.34         2842.73
Permanent Ineff=
       F       F
Bank Sta=304.4,329.1
XS Rating Curve= 0 ,0
Exp/Cntr(USF)=0,0
Exp/Cntr=0.3,0.1

Type RM Length L Ch R = 1 ,6758    ,184.1,200.7,206.7
XS GIS Cut Line= 5
 2307102.3449177576557.9000973842306909.54833261 576554.41582175
2306779.46870894576620.6170587982306629.64485667576750.696682472
2306521.63231201576874.969180088
#Sta/Elev= 30
       0 2873.22     6.2  2872.8    21.8 2867.02    86.2 2852.09   106.2 2849.05
   142.2 2845.64   170.2 2844.45   198.9 2844.72   230.3 2842.42   248.2 2842.21
   266.2 2837.41   273.2 2836.62   311.1 2837.25   357.9 2836.59   369.6 2835.49
   440.8 2835.59   467.8 2832.44     480 2835.83     506 2835.68   525.8 2837.23
   551.1 2836.63     567 2834.98   588.2 2833.81   593.5 2834.98   602.4  2842.4
   614.7 2846.17   651.8 2864.53   678.9  2879.4   690.3 2883.03   701.9 2888.76
#Mann= 3 ,-1,0
       0      .1       0     567    .045       0   593.5      .1       0
#XS Ineff= 2 , 0
          314.39 2838.89
Permanent Ineff=
       F       F
Bank Sta=567,593.5
XS Rating Curve= 0 ,0
Exp/Cntr(USF)=0,0
Exp/Cntr=0.3,0.1

Type RM Length L Ch R = 1 ,6557    ,240.4,243.1,240.2
XS GIS Cut Line= 3
2307117.44344545576545.1244200592306784.11440978576463.824655263
 2306418.2654682576737.921005147
#Sta/Elev= 30
       0 2872.52    10.9 2872.26    34.2 2863.34    67.1 2855.61   110.2 2849.76
   153.6 2845.75   358.3 2843.48   369.7 2841.37   385.4 2836.16     423 2834.47
   441.2 2834.98     453 2833.09     483 2831.46     503 2834.57   518.8 2834.88
   545.5 2834.94   561.2 2832.76   572.9 2832.68   598.9 2833.54   618.9 2832.44
   632.9 2833.01   642.9 2835.36   662.9 2844.63   692.9 2854.19   717.9 2864.96
   732.9 2872.94   752.9 2878.21   778.3 2893.16   792.9 2898.66   800.2 2903.47
#Mann= 3 ,-1,0
       0      .1       0   561.2    .045       0   572.9      .1       0
Bank Sta=561.2,572.9
XS Rating Curve= 0 ,0
Exp/Cntr(USF)=0,0
Exp/Cntr=0.3,0.1