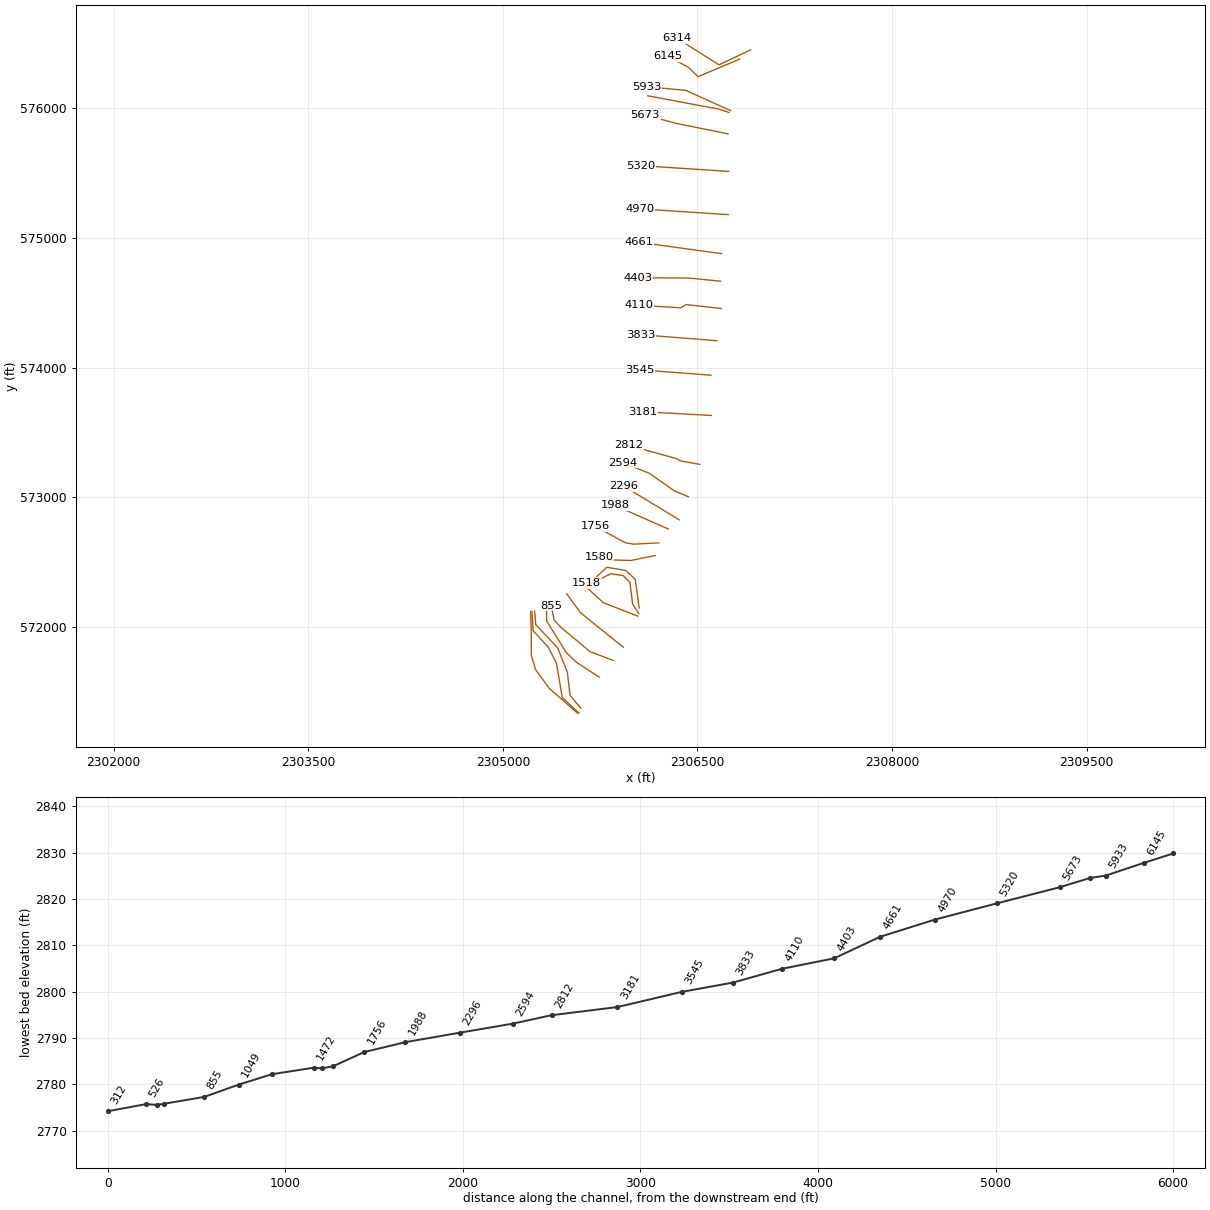
HEC-RAS study MNTNLCKCK.prj: MNTNLCKCK

--- MNTNLCKCK.g01 (geometry) --- (continued)

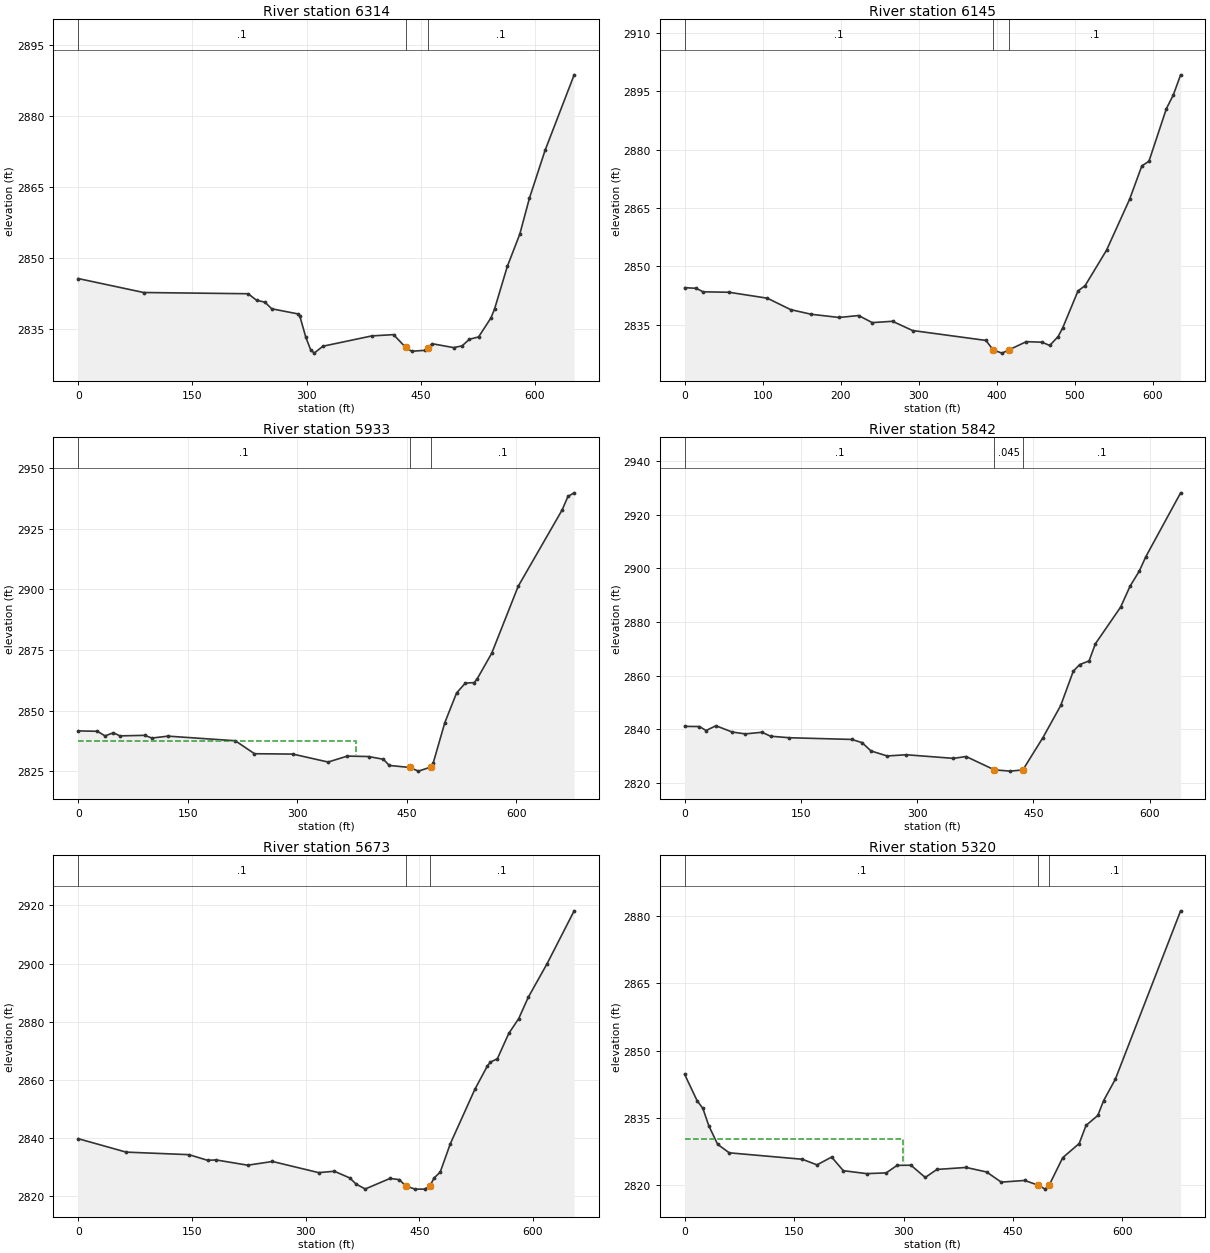
Type RM Length L Ch R = 1 ,6314    ,169.6,168.6,163.8
XS GIS Cut Line= 3
2306909.92800064576449.3459786472306665.64903822 576333.74503159
2306343.93425467576538.155868791
#Sta/Elev= 30
       0 2845.57      86 2842.62   223.2 2842.36   234.2 2840.99   245.3 2840.57
   254.2 2839.18   288.3 2838.11   291.2 2837.56     299 2833.14   305.2 2830.55
   309.9 2829.81   321.4 2831.27   385.7 2833.45   414.2 2833.72   430.22831.008
   437.9 2830.21   455.7  2830.4   458.8 2830.99   465.1 2831.79     493 2830.98
   504.2 2831.34   513.7 2832.73   525.9 2833.24   542.1 2837.25   546.9 2839.16
   563.6 2848.13     580 2854.96   592.6 2862.52   613.2 2872.66   651.4 2888.62
#Mann= 3 ,-1,0
       0      .1       0   430.2    .045       0   458.8      .1       0
Bank Sta=430.2,458.8
XS Rating Curve= 0 ,0
Exp/Cntr(USF)=0,0
Exp/Cntr=0.3,0.1

Type RM Length L Ch R = 1 ,6145    ,197.5,212.4,231.9
XS GIS Cut Line= 4
2306825.93105255576377.6069787532306504.26893391576243.037864965
2306429.87972031576315.1622282082306268.44161593 576402.26911906
#Sta/Elev= 30
       0 2844.56    14.9 2844.39    23.6 2843.49    56.7 2843.38     106 2841.85
   135.8 2838.92   162.3 2837.72     198  2836.9     223  2837.4   240.4 2835.58
   266.4 2835.92   292.1 2833.55   386.2    2831   395.5 2828.54   406.8 2827.74
   415.3 2828.54   437.9 2830.69     458 2830.55   467.9 2829.71   478.7    2832
   484.6 2834.25   504.2 2843.73   513.3 2845.09   540.7 2854.17   570.2 2867.21
     586 2875.85   595.1 2877.03   617.4 2890.53   626.3 2894.05   635.7 2899.24
#Mann= 3 ,-1,0
       0      .1       0   395.5    .045       0   415.3      .1       0
Bank Sta=395.5,415.3
XS Rating Curve= 0 ,0
Exp/Cntr(USF)=0,0
Exp/Cntr=0.3,0.1

Type RM Length L Ch R = 1 ,5933    ,95.3,90.7,88.3
XS GIS Cut Line= 3
2306756.24020471575980.6717673332306408.97406651576137.464170868
 2306111.6492124 576164.17695073
#Sta/Elev= 30
       0 2841.62    26.4 2841.46    36.7 2839.56    48.3 2840.86    57.1 2839.57
    91.1 2839.79     101 2838.67     123 2839.46   215.2 2837.56   241.5 2832.21
   294.1 2832.06   342.4 2828.78   368.7 2831.23   397.9 2831.05     418 2829.92
   426.3 2827.37   454.1 2826.55   466.1 2825.03   483.7 2826.77   486.2 2828.18
   502.3 2845.03   518.4 2857.26   530.4 2861.34   542.5 2861.54   546.5 2863.02
   566.6 2873.68   602.8 2901.25     663 2932.74     671 2938.31   679.5 2939.81
#Mann= 3 ,-1,0
       0      .1       0   454.1    .045       0   483.7      .1       0
#XS Ineff= 2 , 0
          380.56 2837.64
Permanent Ineff=
       F       F
Bank Sta=454.1,483.7
XS Rating Curve= 0 ,0
Exp/Cntr(USF)=0,0
Exp/Cntr=0.3,0.1

Type RM Length L Ch R = 1 ,5842    ,170.7,169,166.7
XS GIS Cut Line= 3
2306742.32311248575967.0586194052306668.64377785575991.854549328
2306116.04876815576095.288999862
#Sta/Elev= 30
       0 2841.15    19.1 2841.09    27.6 2839.61    40.3 2841.38    61.4 2839.04
    78.2 2838.35    99.8 2838.96   110.8 2837.49   135.2 2836.92   215.4 2836.29
   228.8 2835.11   240.4 2832.01   261.3 2830.13   285.8 2830.59   346.8 2829.24
   363.1 2829.93   399.7 2824.96   420.1 2824.49   436.3 2824.94   462.2 2836.95
   485.2 2848.93   501.4 2861.69   509.6 2864.15   521.8 2865.52   529.9  2871.9
   562.5 2885.56   574.7 2893.37   586.6 2898.98     595 2904.32   639.9  2928.1
#Mann= 3 ,-1,0
       0      .1       0   399.7    .045       0   436.3      .1       0
Bank Sta=399.7,436.3
XS Rating Curve= 0 ,0
Exp/Cntr(USF)=0,0
Exp/Cntr=0.3,0.1

Type RM Length L Ch R = 1 ,5673    ,348.5,353.4,357.8
XS GIS Cut Line= 3
2306735.33455091575801.8122847822306328.83572693575884.273474789
2306097.71210986575946.990436203
#Sta/Elev= 30
       0 2839.84    63.2 2835.23   146.1 2834.35   170.6 2832.42     182 2832.54
   223.6 2830.73   256.3 2832.01   317.2 2828.18   337.9 2828.65   358.4 2826.34
   366.5 2824.27   378.7 2822.56   411.4 2826.19   423.8 2825.76     432 2823.59
   444.5 2822.51   456.9 2822.52   464.1  2823.6   469.3 2826.29   477.6 2828.37
     491 2838.16   523.2 2856.75   539.9 2864.88   543.9 2866.16     553 2867.32
     568 2875.99   581.2 2881.12   593.7  2888.4   618.6 2899.97   654.3 2918.13
#Mann= 3 ,-1,0
       0      .1       0     432    .045       0   464.1      .1       0
Bank Sta=432,464.1
XS Rating Curve= 0 ,0
Exp/Cntr(USF)=0,0
Exp/Cntr=0.3,0.1

Type RM Length L Ch R = 1 ,5320    ,350.5,350,347.8
XS GIS Cut Line= 2
2306741.14167696575512.6174071512306062.86935352575556.751565183
#Sta/Elev= 30
       0 2844.66      17  2838.8      25 2837.05      33 2833.22    45.1 2829.06
    61.1 2827.15   161.3 2825.71   181.3 2824.46   201.4  2826.2   217.4 2823.16
   249.5  2822.5   276.2 2822.67   291.2 2824.35   310.1 2824.38   329.7 2821.65
   345.7 2823.44   385.8 2823.88   413.8 2822.87   433.9  2820.6     466 2820.98
   484.9 2819.89     494 2819.04   499.62819.946   518.1 2826.06   540.7 2829.23
   550.1 2833.28   566.2 2835.49   574.2 2838.82   590.2 2843.58   679.7  2881.2
#Mann= 3 ,-1,0
       0      .1       0   484.9    .045       0   499.6      .1       0
#XS Ineff= 2 , 0
          299.72  2830.3
Permanent Ineff=
       F       F
Bank Sta=484.9,499.6
XS Rating Curve= 0 ,0
Exp/Cntr(USF)=0,0
Exp/Cntr=0.3,0.1

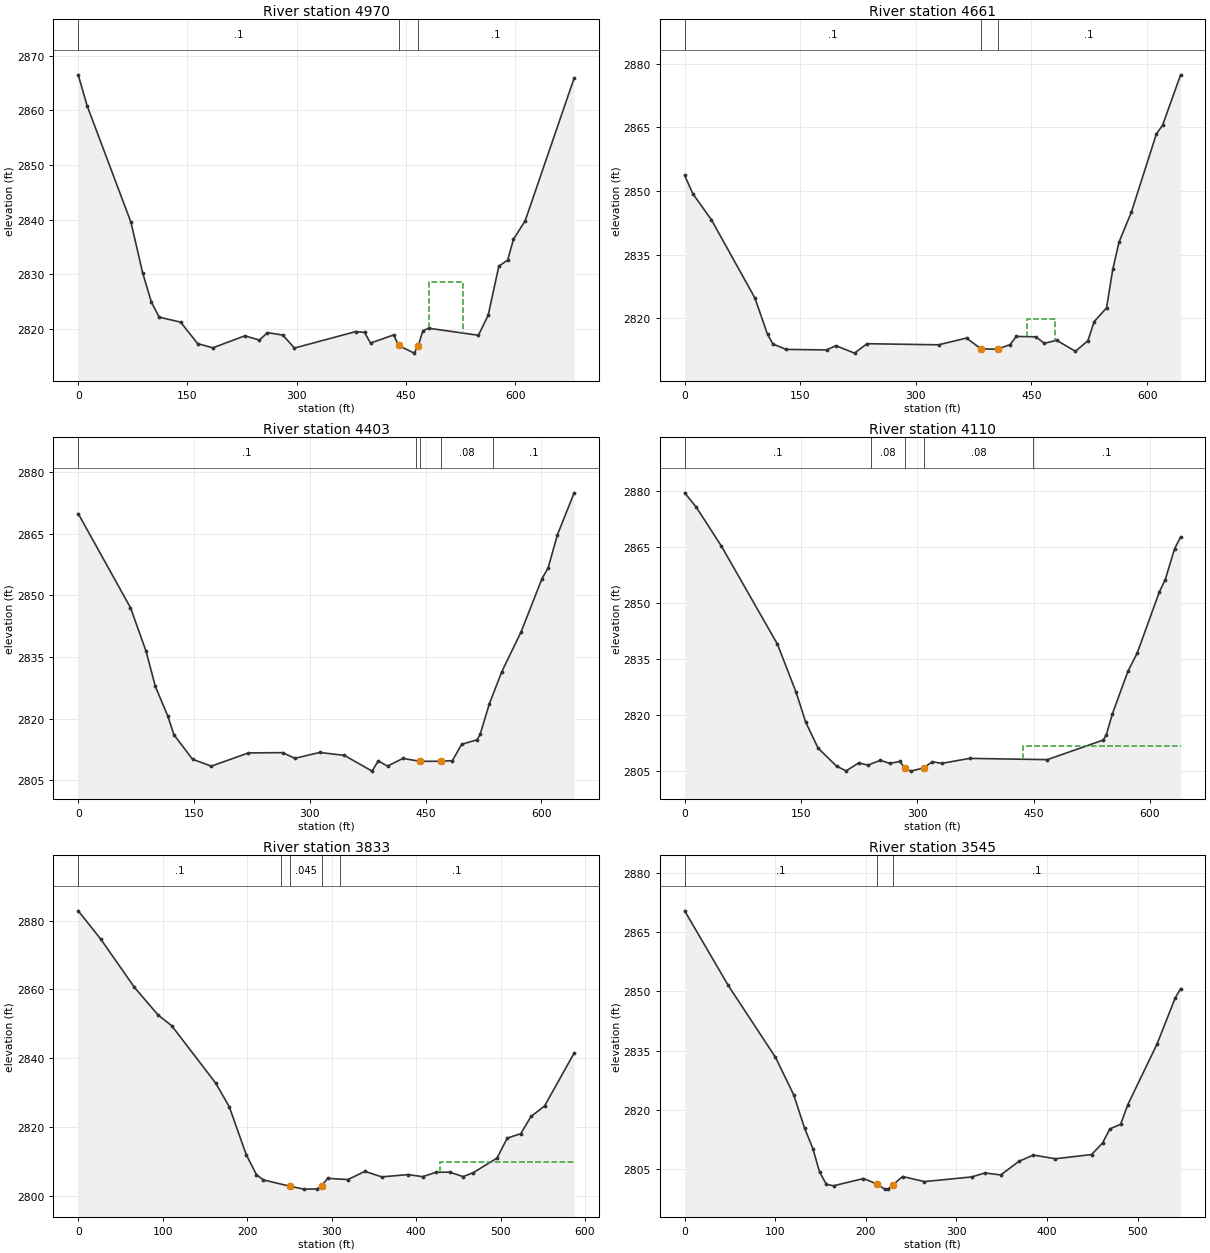
Type RM Length L Ch R = 1 ,4970    ,308.6,308.8,306
XS GIS Cut Line= 2
2306736.49597612575179.2883714882306057.06222746 575223.42252952
#Sta/Elev= 30
       0 2866.52    12.3 2860.83    72.5 2839.47    88.5 2830.23   100.5 2824.86
   111.2 2822.12   140.6 2821.21   163.9 2817.28   184.7  2816.5   228.8  2818.7
   248.8 2817.92   259.8 2819.28   280.9 2818.84   296.9 2816.46   381.1 2819.48
   393.1 2819.33   401.3 2817.37   433.2 2818.87   439.9 2816.93   461.3 2815.53
   466.62816.811   473.3 2819.65   481.3 2820.09   549.5  2818.8   562.9 2822.49
   577.5 2831.45   589.6 2832.58   597.6  2836.4   613.6 2839.76   680.9 2865.92
#Mann= 3 ,-1,0
       0      .1       0   439.9    .045       0   466.6      .1       0
#XS Ineff= 1 ,-1
   481.4  527.912828.555
Permanent Ineff=
       F
Bank Sta=439.9,466.6
XS Rating Curve= 0 ,0
Exp/Cntr(USF)=0,0
Exp/Cntr=0.3,0.1

Type RM Length L Ch R = 1 ,4661    ,253.4,257.8,260.9
XS GIS Cut Line= 2
2306686.55469203574878.4792417432306048.93225098574965.586132595
#Sta/Elev= 30
       0 2853.69    10.5 2849.39    34.7 2843.23    91.2 2824.77   107.5 2816.22
   114.6 2813.95   131.6 2812.68   184.1 2812.57   196.2 2813.56   220.4 2811.81
   236.6 2814.03   329.4 2813.77   365.7 2815.36   384.6 2812.81   406.1 2812.74
   422.3 2813.83   430.3 2815.74   455.6 2815.66   466.7 2814.13   482.8 2814.82
     507 2812.25   523.2 2814.73   531.3 2819.23   547.4 2822.47   555.5 2831.58
   563.6 2837.98   579.7 2845.09     612 2863.44   620.1 2865.52   643.5 2877.39
#Mann= 3 ,-1,0
       0      .1       0   384.6    .045       0   406.1      .1       0
#XS Ineff= 1 ,-1
  444.19  480.23 2819.96
Permanent Ineff=
       F
Bank Sta=384.6,406.1
XS Rating Curve= 0 ,0
Exp/Cntr(USF)=0,0
Exp/Cntr=0.3,0.1

Type RM Length L Ch R = 1 ,4403    ,278.2,292.8,305.1
XS GIS Cut Line= 3
2306679.58614076574665.9384280622306433.36399595574690.328357501
2306038.47942408574692.651207923
#Sta/Elev= 30
       0 2869.96    67.7 2847.02    87.8 2836.46    99.9 2827.82     116 2820.63
     124 2816.03   148.1 2810.08   172.3 2808.39   220.5 2811.62   264.6 2811.69
   280.6  2810.3   312.6 2811.73   344.6 2811.03   380.6 2807.18   388.6 2809.67
   400.6 2808.41   420.6 2810.28   442.9 2809.56   470.2 2809.59   484.6 2809.74
   496.6 2813.72   516.6 2814.82   520.6 2816.18   532.6 2823.66   548.6 2831.44
   573.6 2841.13   600.6 2854.08   608.6 2856.73   620.6 2864.77   642.3 2875.02
#Mann= 5 ,-1,0
       0      .1       0  437.43     .08       0   442.9    .045       0
   470.2     .08       0  537.43      .1       0
Bank Sta=442.9,470.2
XS Rating Curve= 0 ,0
Exp/Cntr(USF)=0,0
Exp/Cntr=0.3,0.1

Type RM Length L Ch R = 1 ,4110    ,290.1,277.8,263.8
XS GIS Cut Line= 4
2306683.07041639574455.7204648042306412.45834214574485.917520299
2306371.80845975574461.5275908612306052.41652662574478.948969031
#Sta/Elev= 30
       0 2879.63      15 2875.76    47.4 2865.32   119.6 2839.02   143.8 2826.04
     156 2818.13     172 2811.11   195.8 2806.29   208.2    2805   224.3 2807.12
   236.4 2806.55   252.5 2807.84   264.5    2807   277.3 2807.52   284.7 2805.67
   291.3 2804.93     308 2805.75   319.3 2807.46   331.3    2807   367.4 2808.35
   467.6 2808.01   539.7 2813.26   543.7 2814.65   551.7 2820.36   571.7 2831.76
   583.7 2836.66     612 2852.94   619.8 2856.35   631.8 2864.62   639.6  2867.8
#Mann= 5 ,-1,0
       0      .1       0     240     .08       0   284.7    .045       0
     308     .08       0   449.7      .1       0
#XS Ineff= 2 , 0
                          436.63         2811.58
Permanent Ineff=
       F       F
Bank Sta=284.7,308
XS Rating Curve= 0 ,0
Exp/Cntr(USF)=0,0
Exp/Cntr=0.3,0.1

Type RM Length L Ch R = 1 ,3833    ,285.5,287.8,286.6
XS GIS Cut Line= 2
2306650.55051047574207.1754695712306065.19220394574253.632478025
#Sta/Elev= 30
       0 2882.82    26.5 2874.66    66.6 2860.57    94.7 2852.51   110.7 2849.43
   162.9 2832.71   178.8 2825.92     199 2811.93     211 2806.17   219.1 2804.63
   251.2 2802.75   267.2 2801.94   283.3    2802   288.1  2802.9   295.3 2805.07
   319.4 2804.72   339.4  2807.1   359.5  2805.5   390.7 2806.17   407.7 2805.56
   423.7 2806.83   439.8 2806.88   455.8 2805.58   467.8 2806.73   495.9 2810.97
     508 2816.77     524 2818.05   536.1 2823.06   552.1 2826.08   587.2 2841.48
#Mann= 5 ,-1,0
       0      .1       0     240     .08       0   251.2    .045       0
   288.1     .08       0     310      .1       0
#XS Ineff= 2 , 0
                          428.18         2809.74
Permanent Ineff=
       F       F
Bank Sta=251.2,288.1
XS Rating Curve= 0 ,0
Exp/Cntr(USF)=0,0
Exp/Cntr=0.3,0.1

Type RM Length L Ch R = 1 ,3545    ,362.1,363.4,358
XS GIS Cut Line= 2
2306604.09350202573941.2090961672306058.22365268573983.020403776
#Sta/Elev= 30
       0 2870.35    48.1 2851.47   100.2 2833.31   120.3 2823.84   132.3 2815.41
   141.5  2810.2   148.9 2804.29   156.4 2801.15   164.4 2800.79   197.4 2802.62
   212.8 2801.19   220.6 2799.94   224.6 2799.95   230.2  2801.1   240.6 2803.13
   264.7 2801.85   316.8 2803.02   331.5 2804.03   348.9 2803.53     369 2806.97
     385 2808.57   409.1 2807.62   449.2 2808.69   461.3  2811.6   469.3 2815.16
   481.3 2816.36   489.3 2821.35   521.6 2836.71   541.5  2848.3   547.5 2850.66
#Mann= 3 ,-1,0
       0      .1       0   212.8    .045       0   230.2      .1       0
Bank Sta=212.8,230.2
XS Rating Curve= 0 ,0
Exp/Cntr(USF)=0,0
Exp/Cntr=0.3,0.1

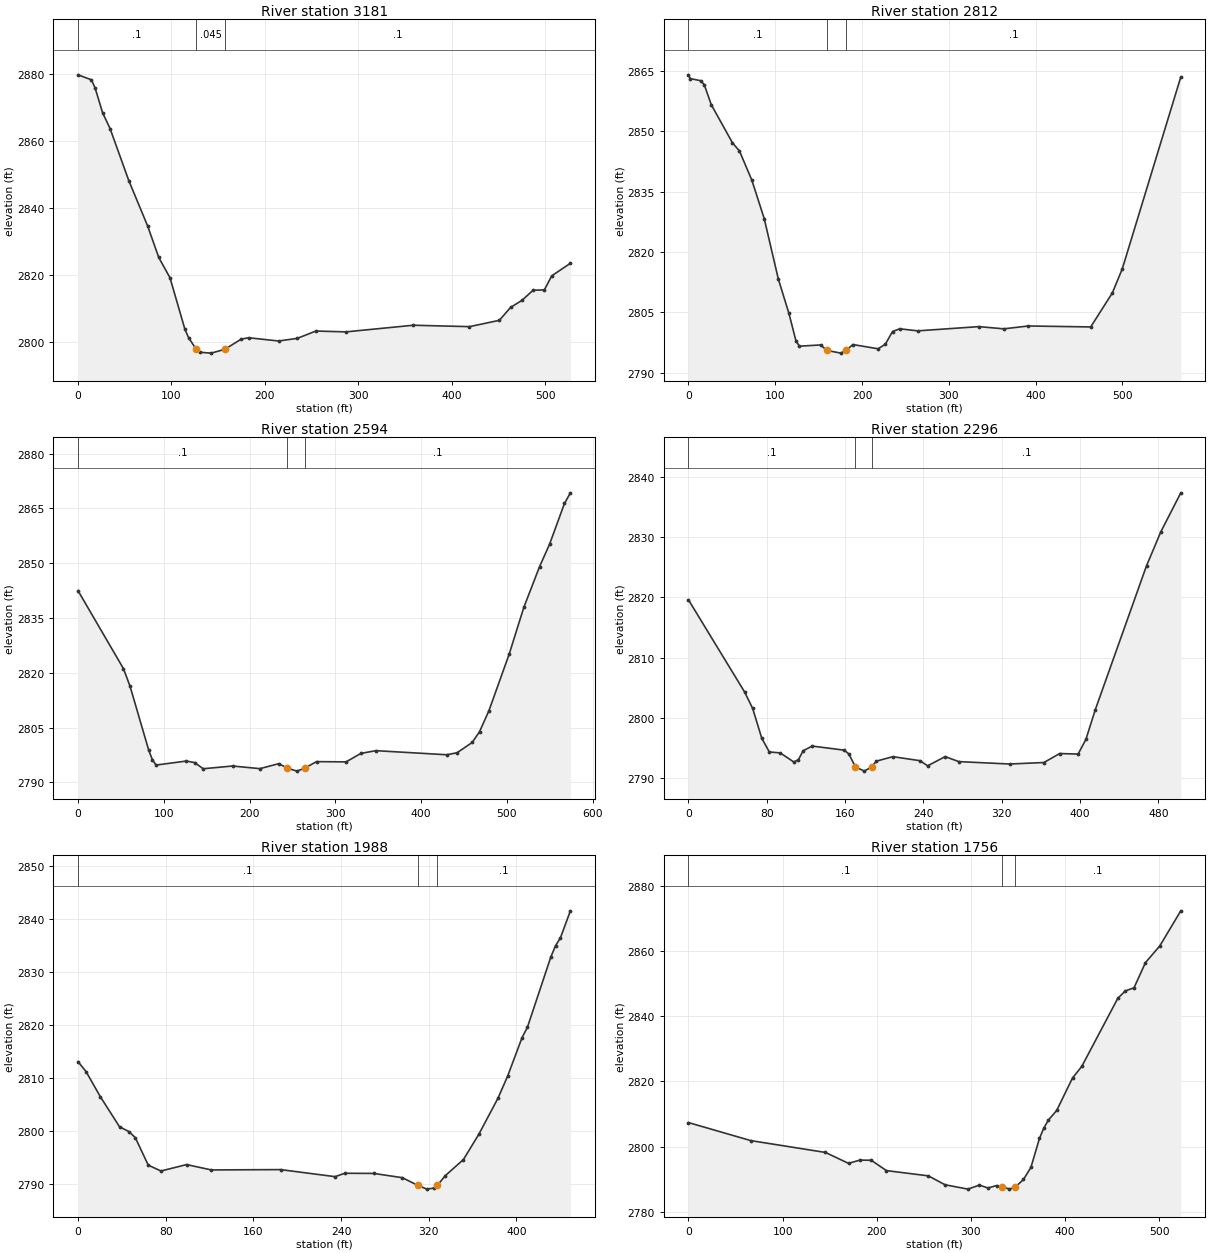
Type RM Length L Ch R = 1 ,3181    ,379.2,369.4,359.4
XS GIS Cut Line= 2
2306606.41635244573631.1085647312306080.29073169573660.144195015
#Sta/Elev= 30
       0 2879.69    14.3 2878.21    18.3 2875.75    26.3 2868.37    34.3 2863.65
    54.3 2848.15    74.4 2834.66    86.4  2825.2    98.4 2819.15   114.4 2803.76
   118.4 2801.23   126.4 2797.84   130.4 2796.92   142.5 2796.66   157.1  2797.8
   174.5 2800.81   182.5 2801.25   214.6 2800.28   234.6 2801.06   254.6 2803.25
   286.7    2803   358.8 2804.98   418.9 2804.56   450.9 2806.45   462.9  2810.3
   475.1  2812.4     487 2815.43     499 2815.51     507 2819.73   526.9 2823.46
#Mann= 3 ,-1,0
       0      .1       0   126.4    .045       0   157.1      .1       0
Bank Sta=126.4,157.1
XS Rating Curve= 0 ,0
Exp/Cntr(USF)=0,0
Exp/Cntr=0.3,0.1

Type RM Length L Ch R = 1 ,2812    ,221.8,218.2,215.4
XS GIS Cut Line= 4
2306518.07758199573254.167371657 2306363.5530623 573282.01898136
2306339.96150612573297.9592220242305972.18787779573400.237835508
#Sta/Elev= 30
       0    2864     1.9 2863.08    14.1 2862.54    18.2 2861.55    26.3 2856.58
    50.7 2847.12    58.8 2845.08      73 2837.86    87.3  2828.3   103.5 2813.34
   115.7 2804.81   123.9 2797.92   127.9 2796.64   152.3 2796.94   159.42795.585
   175.6 2794.91   181.9 2795.64   189.4 2797.04   218.5 2795.99   226.8 2797.12
   235.1 2800.27   243.4 2800.95   264.1 2800.44   334.7 2801.49   363.3 2800.94
   391.6 2801.65   463.4 2801.41   488.3 2809.84   499.8 2815.84   567.2 2863.47
#Mann= 3 ,-1,0
       0      .1       0   159.4    .045       0   181.9      .1       0
Bank Sta=159.4,181.9
XS Rating Curve= 0 ,0
Exp/Cntr(USF)=0,0
Exp/Cntr=0.3,0.1

Type RM Length L Ch R = 1 ,2594    ,290.4,298.2,291
XS GIS Cut Line= 4
2306432.20257074573003.9389505912306320.70575045573050.395959046
2306130.23201578573185.1212835642305925.82117858 573266.42104836
#Sta/Elev= 30
       0 2842.46      53 2821.12    60.7 2816.28    82.4 2798.84    86.7  2796.2
      91 2794.75   126.3 2795.85   136.1 2795.42   145.9 2793.74   180.2 2794.49
   212.1 2793.77   234.1 2795.14   243.9 2793.93   255.2 2793.09   264.1 2793.88
   278.1 2795.69   312.6 2795.62   329.8 2797.94   347.3 2798.69     430 2797.57
     442 2798.12   459.6 2800.93   468.2 2803.89   479.2 2809.67   502.7 2825.08
   519.9 2837.95   538.2 2849.06   549.8 2855.16   567.2 2866.32   574.1 2869.24
#Mann= 3 ,-1,0
       0      .1       0   243.9    .045       0   264.1      .1       0
Bank Sta=243.9,264.1
XS Rating Curve= 0 ,0
Exp/Cntr(USF)=0,0
Exp/Cntr=0.3,0.1

Type RM Length L Ch R = 1 ,2296    ,301.2,307.9,309.2
XS GIS Cut Line= 2
2306360.19420763572826.2408932512305930.46687942573087.561565809
#Sta/Elev= 30
       0 2819.58    57.5 2804.24    65.6 2801.54    74.9 2796.59    82.6 2794.32
    93.7 2794.17   107.7 2792.65   112.4 2793.05   117.1 2794.52   126.4  2795.3
   159.2 2794.62   163.9 2793.98   170.5 2791.85   179.7 2791.14   187.3 2791.88
     192  2792.8   208.8 2793.54   236.6 2792.87   244.3 2792.02   262.2 2793.55
   276.2 2792.72   328.2 2792.32   363.1 2792.57   379.2 2794.06     398 2793.97
     406 2796.42   415.5 2801.31   467.9 2825.24   482.5 2830.87   502.9 2837.34
#Mann= 3 ,-1,0
       0      .1       0   170.5    .045       0   187.3      .1       0
Bank Sta=170.5,187.3
XS Rating Curve= 0 ,0
Exp/Cntr(USF)=0,0
Exp/Cntr=0.3,0.1

Type RM Length L Ch R = 1 ,1988    ,232.3,231.3,229.1
XS GIS Cut Line= 2
2306274.83740574572756.0743855052305863.76290788572937.539704377
#Sta/Elev= 30
       0 2813.12     7.3 2811.26    20.4  2806.5    37.9 2800.84    46.6 2799.92
    52.3 2798.78    64.1 2793.61    75.7 2792.51    99.1 2793.72   121.6 2792.71
   184.9 2792.77   234.6 2791.44   243.4 2792.08   269.8 2792.05   295.9 2791.25
   309.8 2789.83   318.3 2789.09   324.4 2789.28   327.92789.803   335.2 2791.64
   351.7 2794.67   365.8 2799.45   383.3 2806.26   392.1 2810.43   405.2 2817.66
   410.1 2819.61   431.4 2832.82   435.8 2835.01   440.2 2836.45   449.3 2841.56
#Mann= 3 ,-1,0
       0      .1       0   309.8    .045       0   327.9      .1       0
Bank Sta=309.8,327.9
XS Rating Curve= 0 ,0
Exp/Cntr(USF)=0,0
Exp/Cntr=0.3,0.1

Type RM Length L Ch R = 1 ,1756    ,168.6,176.2,183.7
XS GIS Cut Line= 4
 2306202.0043866572648.6765437232306008.81171719572639.418109087
2305943.38544576572649.9110016752305712.54180882572776.442941705
#Sta/Elev= 30
       0 2807.37    66.2 2801.84   145.5 2798.21     170 2794.86     182 2795.86
   194.1 2795.81   210.3 2792.64   254.8 2791.03   272.5  2788.3   296.9 2786.96
     309  2788.2   318.1 2787.31   327.2 2788.05   333.1 2787.64   340.9    2787
   346.9 2787.53   355.8 2789.92   363.7  2793.6   372.8 2802.52   377.4 2805.67
   382.3 2808.14   391.1 2811.08   407.9 2821.05   417.7 2824.58     456 2845.48
     464 2847.75   473.2 2848.69   485.4 2856.44   500.5  2861.5   522.9  2872.3
#Mann= 3 ,-1,0
       0      .1       0   333.1    .045       0   346.9      .1       0
Bank Sta=333.1,346.9
XS Rating Curve= 0 ,0
Exp/Cntr(USF)=0,0
Exp/Cntr=0.3,0.1

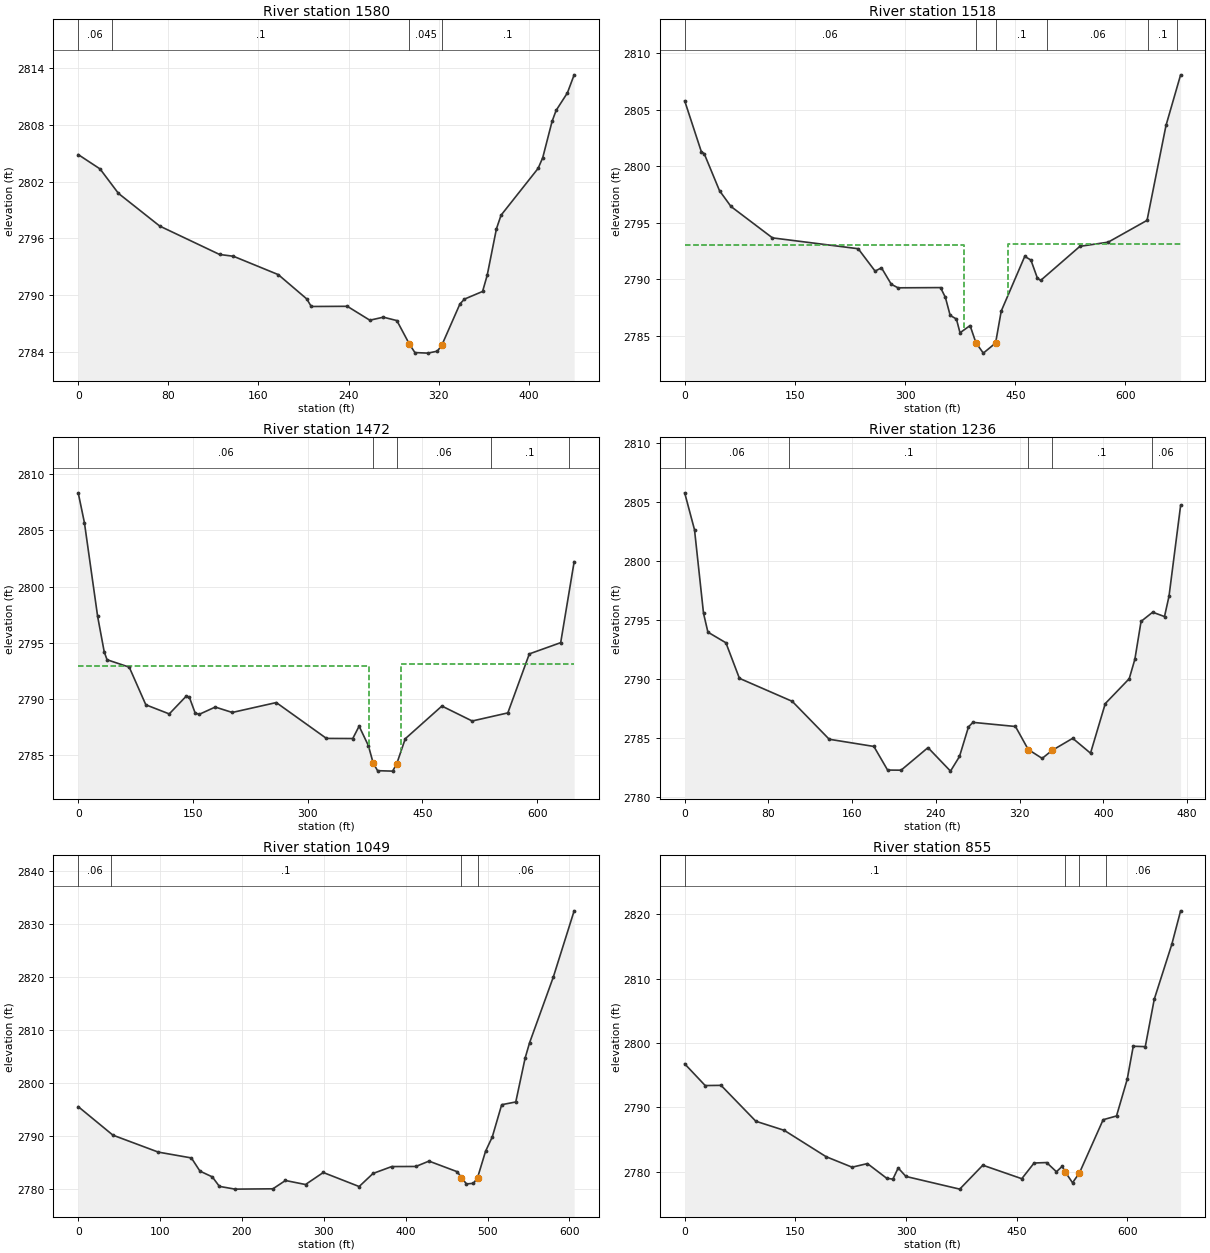
Type RM Length L Ch R = 1 ,1580    ,66,62.4,58.6
BEGIN DESCRIPTION:
xs 4
END DESCRIPTION:
XS GIS Cut Line= 4
2306175.20430447572551.5679089672305987.06056808572513.361435368
2305822.39004964572518.0029972662305741.01458147572537.285230468
#Sta/Elev= 30
       0 2804.87    19.4 2803.35    35.7 2800.77    72.4 2797.31   125.5 2794.31
   137.8 2794.12   177.6 2792.18   202.9 2789.61   206.9 2788.81   238.9 2788.83
   258.9 2787.36   270.9 2787.68   282.9 2787.32     294 2784.84   298.9 2783.94
   310.4 2783.88   318.9 2784.09     323 2784.77   338.9 2789.08   342.9 2789.59
     359  2790.4   363.1 2792.11   371.3 2797.02   375.4 2798.46   408.3 2803.41
   412.4 2804.54   420.7 2808.38   424.3 2809.54   434.3 2811.39   440.3  2813.3
#Mann= 4 ,-1,0
       0     .06       0      30      .1       0     294    .045       0
     323      .1       0
Bank Sta=294,323
XS Rating Curve= 0 ,0
Exp/Cntr(USF)=0,0
Exp/Cntr=0.5,0.3

Type RM Length L Ch R = 1 ,1518    ,44,45.9,48.3
BEGIN DESCRIPTION:
xs 3
END DESCRIPTION:
XS GIS Cut Line= 6
2306051.25510141572146.8071445992306019.98973394572368.300281486
2305948.49610168572435.7942699852305801.50919339572460.792043503
2305687.51934615572355.3014392572305645.52308664572339.802819675
#Sta/Elev= 30
       0 2805.78    22.6 2801.29    26.6  2801.1    47.4 2797.83      63 2796.43
   119.5 2793.65   236.2 2792.69   259.2 2790.71   267.9    2791   281.3 2789.54
   290.5 2789.23   348.3 2789.25   354.9 2788.38   361.4 2786.79   369.9 2786.47
   374.8 2785.25   388.5 2785.89   396.4 2784.38   406.5 2783.45   423.2 2784.34
   430.9 2787.17   462.9 2792.01   471.3 2791.69     480 2790.11   484.5 2789.88
     538  2792.9   576.5 2793.27   629.4  2795.2   655.2  2803.6   675.1 2808.08
#Mann= 6 ,-1,0
       0     .06       0   396.4    .045       0   423.2      .1       0
  493.65     .06       0  630.34      .1       0  670.34     .06       0
#XS Ineff= 2 , 0
             380 2792.98   439.6          2793.1
Permanent Ineff=
       F       F
Bank Sta=396.4,423.2
XS Rating Curve= 0 ,0
Exp/Cntr(USF)=0,0
Exp/Cntr=0.5,0.3

Type RM Length L Ch R = 1 ,1472    ,251.2,235.7,219.1
BEGIN DESCRIPTION:
xs 2
END DESCRIPTION:
XS GIS Cut Line= 6
2306048.98715122572102.8239267242305999.99151512572176.817336337
2305979.49334084 572345.802285322305926.99801645572396.797743297
2305833.00638802572411.2964519372305643.02330928572317.804778979
#Sta/Elev= 30
       0 2808.34     8.1 2805.69    25.4 2797.34      34 2794.19    37.7 2793.49
    66.7 2792.83    88.4 2789.48     119 2788.67   141.2 2790.25   145.2 2790.17
   152.8 2788.76   158.1 2788.63   179.1 2789.28   201.4  2788.8   258.9 2789.68
   324.5 2786.49   358.9 2786.48   367.2 2787.58   379.3 2785.85   385.5 2784.32
   391.3 2783.62     411 2783.58   416.3 2784.22   427.5 2786.46   475.4 2789.37
     515 2788.04   561.6 2788.76   589.7 2794.01   630.7 2795.01   648.3 2802.21
#Mann= 5 ,-1,0
       0     .06       0   385.5    .045       0   416.3     .06       0
  539.29      .1       0  642.15     .06       0
#XS Ineff= 2 ,-1
       0   380.5 2792.95   421.3648.2629  2793.1
Permanent Ineff=
       F       F
Bank Sta=385.5,416.3
XS Rating Curve= 0 ,0
Exp/Cntr(USF)=0,0
Exp/Cntr=0.5,0.3

Type RM Length L Ch R = 1 ,1236    ,191,187.1,181.7
BEGIN DESCRIPTION:
xs 1
END DESCRIPTION:
XS GIS Cut Line= 3
2306040.90762393572083.912030906 2305774.2647064572187.606498833
2305636.00541583572314.755667839
#Sta/Elev= 30
       0 2805.74     9.4 2802.61      18 2795.54    22.2 2793.94    39.4 2793.04
    52.3 2790.03   102.8 2788.08   138.1 2784.87   180.8 2784.26   193.9 2782.26
   206.8 2782.25   232.5 2784.16     254 2782.17   262.6 2783.41   271.2 2785.92
   275.5  2786.3   316.1 2785.95   328.3    2784   341.6 2783.25     351 2783.92
   370.8 2784.95   387.8 2783.69   401.9 2787.89   424.8    2790   430.2 2791.65
   436.1 2794.85   447.2 2795.63   458.5 2795.26   462.8 2796.98   473.9 2804.67
#Mann= 5 ,-1,0
       0     .06       0     100      .1       0   328.3    .045       0
     351      .1       0   446.1     .06       0
Bank Sta=328.3,351
XS Rating Curve= 0 ,0
Exp/Cntr(USF)=0,0
Exp/Cntr=0.3,0.1

Type RM Length L Ch R = 1 ,1049    ,191.8,194.1,196.3
XS GIS Cut Line= 3
2305929.18917931571843.8099593372305597.73721933 572111.07010584
2305492.19106448572256.736144118
#Sta/Elev= 30
       0 2795.51    42.4 2790.12    97.8 2786.92   138.2 2785.82   148.7 2783.33
   163.8 2782.24   172.4 2780.45   191.4 2779.93   237.8 2779.99   253.1 2781.56
   277.6  2780.8   299.3 2783.07   343.1 2780.42   360.1 2782.89   382.9 2784.19
   412.4 2784.21   428.4 2785.22     463 2783.21   467.9 2782.12   474.2 2780.91
   482.7 2781.03   487.7 2782.08   497.5 2787.08   505.7 2789.78   517.2 2795.87
   534.4 2796.39   545.8 2804.66   551.2 2807.54   580.2 2819.95   605.7 2832.48
#Mann= 4 ,-1,0
       0     .06       0      40      .1       0   467.9    .045       0
   487.7     .06       0
Bank Sta=467.9,487.7
XS Rating Curve= 0 ,0
Exp/Cntr(USF)=0,0
Exp/Cntr=0.3,0.1

Type RM Length L Ch R = 1 ,855     ,224.4,224,213
XS GIS Cut Line= 5
2305850.18387042571742.5844073132305671.18746745571811.096823622
2305447.22854314571998.2833405082305394.66888631572054.902269046
2305373.06587216572164.151797755
#Sta/Elev= 30
       0 2796.76    27.8 2793.38    49.3 2793.41    96.5 2787.83   134.9 2786.42
   191.7 2782.32   226.9 2780.69   247.7 2781.25   273.8 2778.97   282.2 2778.83
   289.4 2780.57   299.9 2779.25   372.8 2777.28   404.1    2781   456.9  2778.9
   473.6 2781.34   490.6 2781.41   503.9 2779.98   511.6 2780.82   516.1  2779.9
   525.7 2778.27   535.1 2779.81   567.2 2788.07   585.3 2788.65   599.8 2794.35
     608 2799.49   624.3 2799.43   636.5 2806.81   660.2 2815.31   672.2 2820.54
#Mann= 4 ,-1,0
       0      .1       0   516.1    .045       0   535.1      .1       0
   570.8     .06       0
Bank Sta=516.1,535.1
XS Rating Curve= 0 ,0
Exp/Cntr(USF)=0,0
Exp/Cntr=0.3,0.1

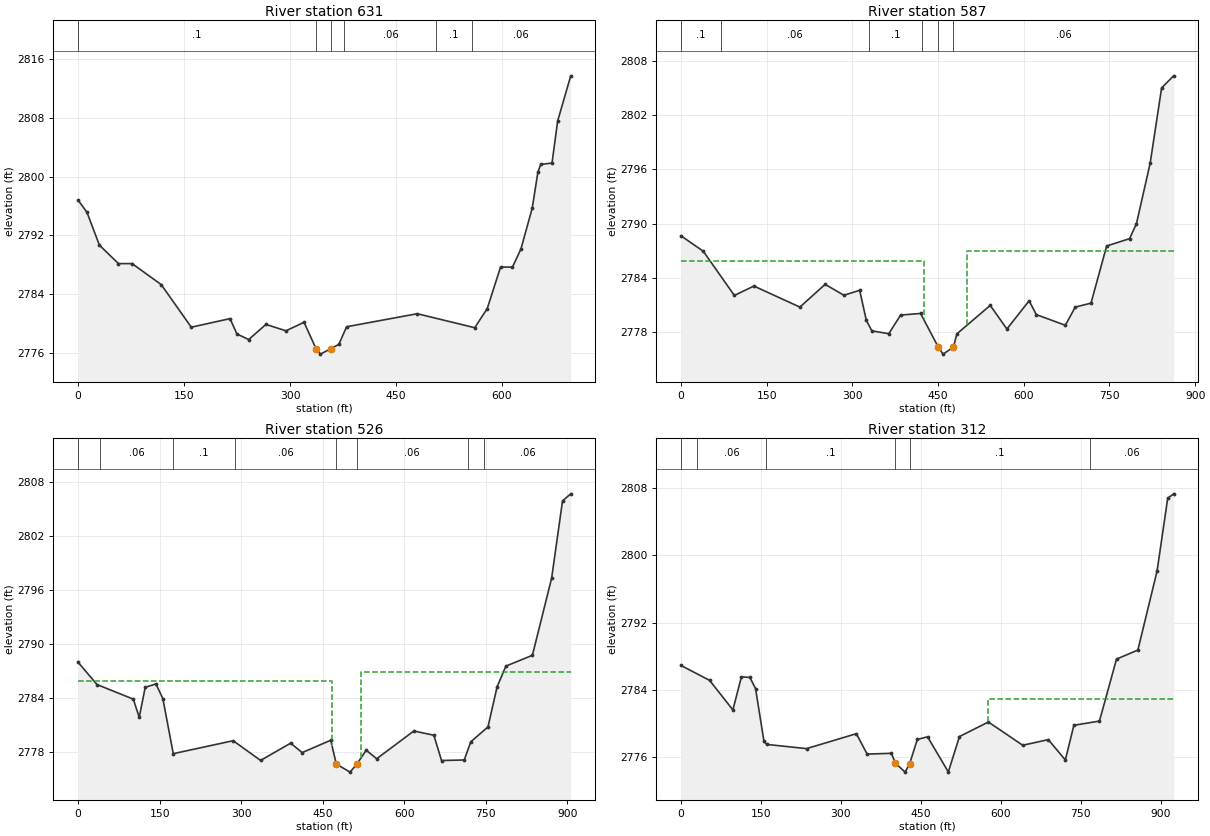
Type RM Length L Ch R = 1 ,631     ,48,43.6,44.7
BEGIN DESCRIPTION:
xs 4
END DESCRIPTION:
XS GIS Cut Line= 5
2305742.72458692571613.9173310492305567.46203825571728.218993226
2305489.56757217571802.7267433862305338.01203491572045.723610385
2305336.31867696572139.704977064
#Sta/Elev= 30
       0 2796.82    12.6 2795.16    30.2 2790.68    57.2 2788.16    76.5 2788.16
   117.7  2785.3   160.3 2779.49   215.1 2780.66   224.9 2778.57   241.5 2777.81
     266 2779.87   294.3    2779   319.9 2780.16   337.2 2776.49   343.1 2775.82
   357.5 2776.55   369.2 2777.15   380.1 2779.55   480.2 2781.33   561.5 2779.42
   579.2 2782.03   598.1 2787.69   614.9 2787.68   626.9 2790.15   642.9 2795.72
   650.9 2800.63   654.9 2801.68   670.9 2801.87   678.9 2807.61   697.4 2813.76
#Mann= 6 ,-1,0
       0      .1       0   337.2    .045       0   357.5      .1       0
  377.03     .06       0  507.03      .1       0  557.03     .06       0
Bank Sta=337.2,357.5
XS Rating Curve= 0 ,0
Exp/Cntr(USF)=0,0
Exp/Cntr=0.5,0.3

Type RM Length L Ch R = 1 ,587     ,60.5,61,61.4
BEGIN DESCRIPTION:
xs 3
END DESCRIPTION:
XS GIS Cut Line= 6
2305600.14224756571375.1532944932305518.29661291571472.991754299
2305496.65926122571653.6166031712305422.33966195571839.885978571
2305253.00386613572019.5700730232305245.47783076572122.112304934
#Sta/Elev= 30
       0 2788.65    39.1 2786.94    93.5 2782.05   127.7 2783.09   208.2 2780.76
   252.4 2783.28   285.2 2782.07   312.8 2782.62   324.5 2779.29   334.2 2778.13
   363.8 2777.82   384.5 2779.88   419.4 2780.06   450.3 2776.35   458.8 2775.56
   476.92776.337   482.9  2777.8   541.3 2780.95   570.5 2778.34   609.4 2781.46
     622 2779.93   672.8 2778.75   690.1 2780.76   717.7  2781.2   745.1 2787.52
   785.2 2788.33   797.2 2789.98   821.3 2796.69   841.3 2805.01   862.3 2806.34
#Mann= 6 ,-1,0
       0      .1       0      70     .06       0  329.54      .1       0
  421.37     .06       0   450.3    .045       0   476.9     .06       0
#XS Ineff= 2 ,-1
       0   425.1 2785.84   501.3862.2964 2786.95
Permanent Ineff=
       F       F
Bank Sta=450.3,476.9
XS Rating Curve= 0 ,0
Exp/Cntr(USF)=0,0
Exp/Cntr=0.5,0.3

Type RM Length L Ch R = 1 ,526     ,214.6,214.6,214.6
BEGIN DESCRIPTION:
xs 2
END DESCRIPTION:
XS GIS Cut Line= 6
2305586.97168566571337.5231176452305458.08832996571456.058174717
2305412.93211774 571722.291675922305348.96081709571846.471259519
2305233.24802329 571971.591597542305224.78123349572120.230796092
#Sta/Elev= 30
       0 2787.93    34.9 2785.45   101.6 2783.83   112.5 2781.81   123.5 2785.14
   143.3 2785.52     156 2783.88   175.1 2777.77   285.2 2779.21   335.7 2777.02
     391 2778.94   412.1 2777.89   464.6 2779.26   474.9 2776.62   500.2 2775.72
   512.62776.603   529.9 2778.15   549.2 2777.21   617.5 2780.29   654.3 2779.82
   668.4 2777.01   710.2 2777.07   722.2 2779.09   753.8 2780.74   770.7 2785.22
   786.8  2787.5   835.5  2788.7   870.9 2797.28   890.9 2805.85     906 2806.64
#Mann= 8 ,-1,0
       0      .1       0      40     .06       0   175.1      .1       0
  287.72     .06       0   474.9    .045       0   512.6     .06       0
   716.7      .1       0   746.7     .06       0
#XS Ineff= 2 , 0
           466.9  2785.8   520.6          2786.9
Permanent Ineff=
       F       F
Bank Sta=474.9,512.6
XS Rating Curve= 0 ,0
Exp/Cntr(USF)=0,0
Exp/Cntr=0.5,0.3

Type RM Length L Ch R = 1 ,312     ,,,
BEGIN DESCRIPTION:
xs 1
END DESCRIPTION:
XS GIS Cut Line= 6
2305577.56414145571334.7008543812305358.36836131571526.614756308
2305252.06311171571672.4316915952305219.13670697571781.559204456
2305219.13670697 571963.124807752305213.49218044572120.230796092
#Sta/Elev= 30
       0  2786.9    53.8 2785.12    97.5  2781.6   113.5 2785.54   129.4 2785.47
   140.1 2784.13   155.8 2777.85   161.3 2777.49   235.8 2776.99   329.2 2778.77
   349.4 2776.34   394.9 2776.43   402.6 2775.25   420.7 2774.19   429.3 2775.21
   443.6 2778.08   462.8  2778.4   501.8 2774.21   522.7 2778.43     577 2780.16
   641.4 2777.39   689.4 2778.06   721.4 2775.64   737.4 2779.77   785.4 2780.27
   817.4 2787.65   857.5 2788.73   893.5 2798.13   913.5 2806.81   924.6 2807.34
#Mann= 6 ,-1,0
       0      .1       0      30     .06       0     160      .1       0
   402.6    .045       0   429.3      .1       0  767.34     .06       0
#XS Ineff= 2 , 0
                          575.77         2782.91
Permanent Ineff=
       F       F
Bank Sta=402.6,429.3
XS Rating Curve= 0 ,0
Exp/Cntr(USF)=0,0
Exp/Cntr=0.3,0.1
LCMann Table=0

Chan Stop Cuts=-1
Use User Specified Reach Order=0
Composite Channel Slope=5